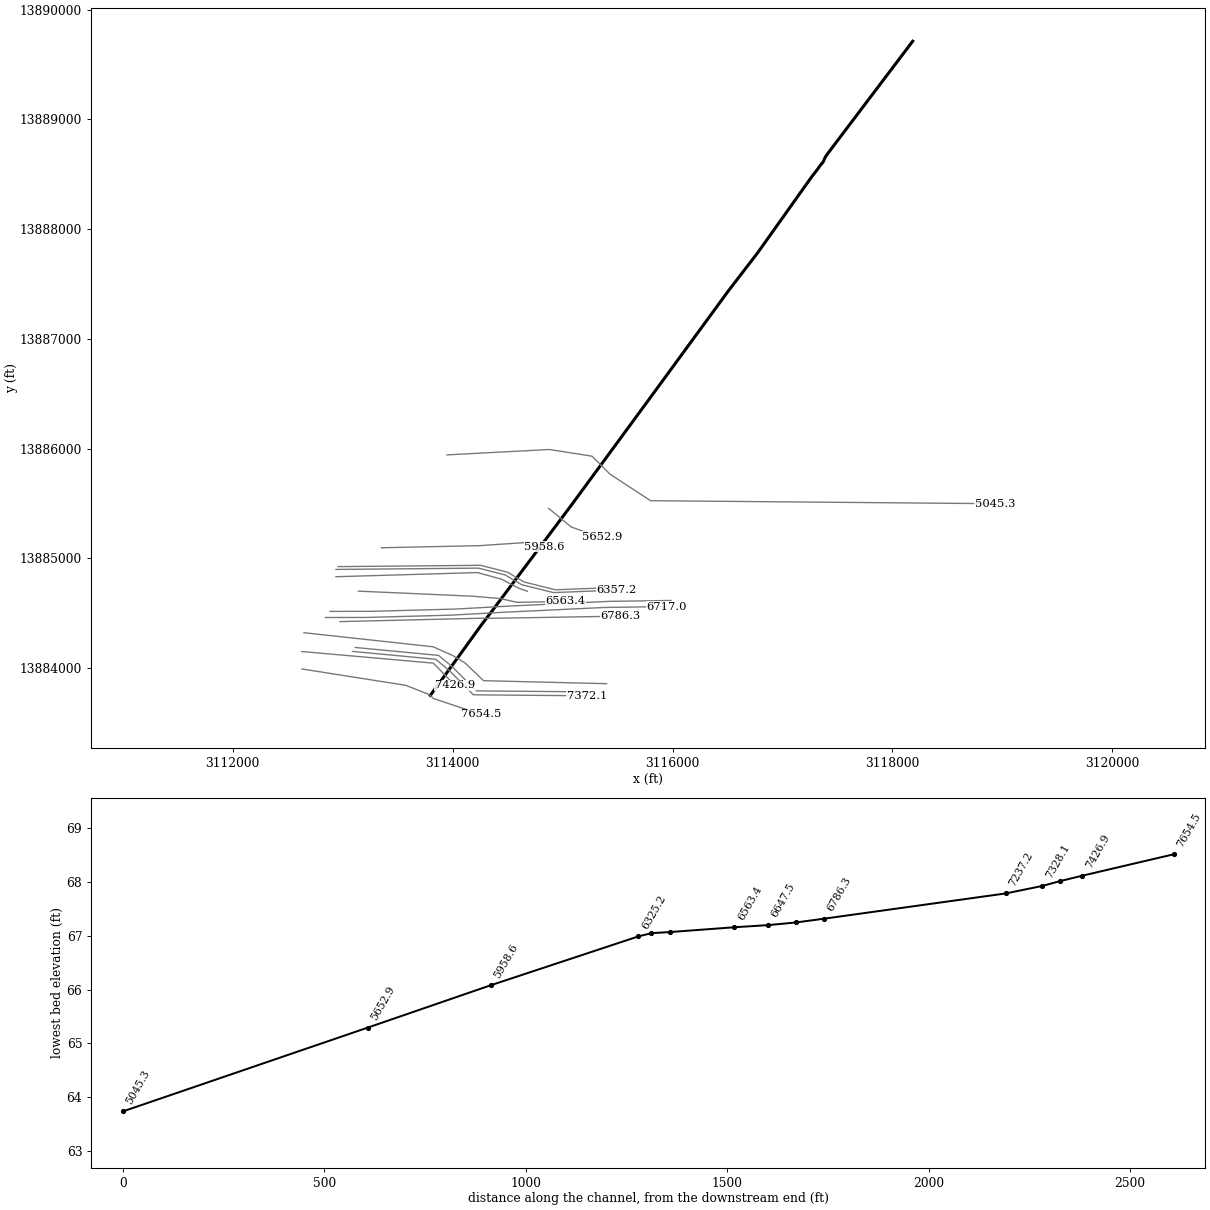
--- P118-23-00.PRJ (project) ---

Proj Title=P118-23-00
Current Plan=p02
Default Exp/Contr=.3,.1
English Units
Geom File=g01
Flow File=f01
Flow File=f02
Plan File=p01
Plan File=p02
Y Axis Title=Elevation
X Axis Title(PF)=Main Channel Distance
X Axis Title(XS)=Station
BEGIN DESCRIPTION:
Greens/Halls Bayou Watershed
Tributary 11.96 to Halls Bayou
HCFCD Unit P118-23-00
Flood Hazard Model
10, 2, 1, 0.2% Event
Filename P118-23-00.prj
Prepared by:  Watershed Concepts  Date:
Reviewed by:                      Date:
STATUS FINAL
END DESCRIPTION:
DSS Export Rating Curves= 0
DSS Export Rating Curve Sorted= 0
DSS Export Volume Flow Curves= 0
DXF OffsetX= 0
DXF OffsetY= 0
DXF ScaleX= 1
DXF ScaleY= 10

--- P118-23-00.p02 (plan) ---

Plan Title=Floodway
Version=Version 3.0.1  Mar 2001
Short Identifier=Floodway0607
Geom File=g01
Flow File=f02
Subcritical Flow
K Sum by GR= 0
Std Step Tol= 0.01
Critical Tol= 0.01
Num of Std Step Trials= 20
Max Error Tol= 0.3
Flow Tol Ratio= 0.001
Split Flow NTrial= 30
Split Flow Tol= 0.02
Split Flow Ratio= 0.02
Log Output Level= 0
Friction Slope Method= 1
Unsteady Friction Slope Method= 2
Parabolic Critical Depth
Global Vel Dist= 0 , 0 , 0
Global Log Level= 0
CheckData=True
Encroach Param=-1 ,0,0, 2
Encroach River=P118-23-00
Encroach Reach=Reach - 1
Encroach Node=7654.5
       1  4988.9  5012.1
Encroach Node=7426.9
       1  4988.9  5012.1
Encroach Node=7372.1
       1  4988.9  5012.1
Encroach Node=7350.1
       1  4988.9  5012.1
Encroach Node=7328.1
       1  4988.9  5012.1
Encroach Node=7237.2
       1  4983.9  5011.2
Encroach Node=6786.3
       1  4977.2 5009.18
Encroach Node=6717.0
       1  4977.2 5009.18
Encroach Node=6682.2
       1  4977.2 5009.18
Encroach Node=6647.5
       1  4977.2 5009.18
Encroach Node=6563.4
       1    4983  5015.7
Encroach Node=6402.4
       1    4983  5015.7
Encroach Node=6357.2
       1  4982.9  5015.7
Encroach Node=6341.2
       1  4982.9  5015.7
Encroach Node=6325.2
       1  4982.9  5015.7
Encroach Node=5958.6
       1  4983.4    5017
Encroach Node=5652.9
       1  4980.5    5035
Encroach Node=5045.3
       1    4830    5100
Encroach Node=4936.5
       1    4830    5100
Encroach Node=4920.5
       1    4830    5100
Encroach Node=4904.5
       1    4830    5100
Encroach Node=4783.1
       1    4830    5120
Encroach Node=4582.1
       1    4770    5125
Encroach Node=4568.5
       1    4770    5125
Encroach Node=4555.0
       1    4770    5125
Encroach Node=4459.7
       1    4725    5140
Encroach Node=4330.8
       1    4725  5023.9
Encroach Node=4303.8
       1    4725  5023.9
Encroach Node=4276.8
       1    4725  5023.9
Encroach Node=3733.5
       1    4520    5150
Encroach Node=3187.4
       1    4450    5300
Encroach Node=2615.4
       1    4480    5325
Encroach Node=2245.0
       1    4500    5200
Encroach Node=2215.5
       1    4510    5200
Encroach Node=2198.5
       1    4510    5200
Encroach Node=2181.5
       1    4510    5200
Encroach Node=2042.4
       1    4590    5090
Encroach Node=1922.1
       1    4537    5040
Encroach Node=1863.5
       1    4550  5020.5
Encroach Node=1846.5
       1    4550  5020.5
Encroach Node=1829.5
       1    4550  5020.5
Encroach Node=1611.4
       1    4740    5140
Encroach Node=1513.8
       1  4932.1    5140
Encroach Node=1443.8
       1    4963    5110
Encroach Node=1414.8
       1    4963    5110
Encroach Node=1385.8
       1    4963    5110
Encroach Node=1010.6
       1    4920    5115
Encroach Reach=P118-23-00_0010
Encroach Node=7654.5
       1  4988.9  5012.1
Encroach Node=7426.9
       1  4988.9  5012.1
Encroach Node=7372.1
       1  4988.9  5012.1
Encroach Node=7350.1
       1  4988.9  5012.1
Encroach Node=7328.1
       1  4988.9  5012.1
Encroach Node=7237.2
       1  4983.9  5011.2
Encroach Node=6786.3
       1  4977.2 5009.18
Encroach Node=6717.0
       1  4977.2 5009.18
Encroach Node=6682.2
       1  4977.2 5009.18
Encroach Node=6647.5
       1  4977.2 5009.18
Encroach Node=6563.4
       1    4983  5015.7
Encroach Node=6402.4
       1    4983  5015.7
Encroach Node=6357.2
       1  4982.9  5015.7
Encroach Node=6341.2
       1  4982.9  5015.7
Encroach Node=6325.2
       1  4982.9  5015.7
Encroach Node=5958.6
       1  4983.4    5017
Encroach Node=5652.9
       1  4980.5    5035
Encroach Node=5045.3
       1    4830    5100
Encroach Node=4936.5
       1    4830    5100
Encroach Node=4920.5
       1    4830    5100
Encroach Node=4904.5
       1    4830    5100
Encroach Node=4783.1
       1    4830    5120
Encroach Node=4582.1
       1    4770    5125
Encroach Node=4568.5
       1    4770    5125
Encroach Node=4555.0
       1    4770    5125
Encroach Node=4459.7
       1    4725    5140
Encroach Node=4330.8
       1    4725  5023.9
Encroach Node=4303.8
       1    4725  5023.9
Encroach Node=4276.8
       1    4725  5023.9
Encroach Node=3733.5
       1    4520    5150
Encroach Node=3187.4
       1    4450    5300
Encroach Node=2615.4
       1    4480    5325
Encroach Node=2245.0
       1    4500    5200
Encroach Node=2215.5
       1    4510    5200
Encroach Node=2198.5
       1    4510    5200
Encroach Node=2181.5
       1    4510    5200
Encroach Node=2042.4
       1    4590    5090
Encroach Node=1922.1
       1    4537    5040
Encroach Node=1863.5
       1    4550  5020.5
Encroach Node=1846.5
       1    4550  5020.5
Encroach Node=1829.5
       1    4550  5020.5
Encroach Node=1611.4
       1    4740    5140
Encroach Node=1513.8
       1  4932.1    5140
Encroach Node=1443.8
       1    4963    5110
Encroach Node=1414.8
       1    4963    5110
Encroach Node=1385.8
       1    4963    5110
Encroach Node=1010.6
       1    4920    5115
Computation Interval=1HOUR
Output Interval=1HOUR
Run HTab= 0
Run UNet= 0
Run PostProcess= 0
UNET Theta= 1
UNET ZTol= 0.02
UNET ZSATol= 0.1
UNET MxIter= 20
UNET MaxInSteps= 20
UNET DtIC= 0
UNET DtMin= 0
UNET MaxCRTS= 20
UNET WFStab= 2
UNET SFStab= 1
UNET WFX= 1
UNET SFX= 1
UNET Convert EG Bridges=-1
UNET Use Existing IB Tables=-1
Instantaneous Interval=1HOUR
Write IC File= 0
Write Velocity= 0
Write Detailed= 0

--- P118-23-00.p01 (plan) ---

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Plan Title=FEMA Effective June 2007
Short Identifier=FEMAeff0607
Geom File= g01
Flow File= f01
Interactive Comp Mode
Encroach Param= -1, 0, 0, 0

--- P118-23-00.f02 (steady flow) ---

Flow Title= Floodway
Number of Profiles= 2
Profile Names=1PCT_100yr, 1PCTFloodway_100yrFW
River Rch & RM=P118-23-00,P118-23-00_0010,7654.5
       7       7
River Rch & RM=P118-23-00,P118-23-00_0010,7426.9
       8       8
River Rch & RM=P118-23-00,P118-23-00_0010,7372.1
      10      10
River Rch & RM=P118-23-00,P118-23-00_0010,7237.2
      23      23
River Rch & RM=P118-23-00,P118-23-00_0010,6786.3
      26      26
River Rch & RM=P118-23-00,P118-23-00_0010,6717
      34      34
River Rch & RM=P118-23-00,P118-23-00_0010,6563.4
      45      45
River Rch & RM=P118-23-00,P118-23-00_0010,6402.4
      49      49
River Rch & RM=P118-23-00,P118-23-00_0010,6357.2
      97      97
River Rch & RM=P118-23-00,P118-23-00_0010,5958.6
     166     166
River Rch & RM=P118-23-00,P118-23-00_0010,5652.9
     449     449
River Rch & RM=P118-23-00,P118-23-00_0010,5045.3
     461     461
River Rch & RM=P118-23-00,P118-23-00_0010,4582.1
     468     468
River Rch & RM=P118-23-00,P118-23-00_0010,4330.8
     482     482
River Rch & RM=P118-23-00,P118-23-00_0010,3733.5
     496     496
River Rch & RM=P118-23-00,P118-23-00_0010,3187.4
     885     885
River Rch & RM=P118-23-00,P118-23-00_0010,2615.4
     935     935
River Rch & RM=P118-23-00,P118-23-00_0010,2245
     963     963
River Rch & RM=P118-23-00,P118-23-00_0010,2042.4
     994     994
River Rch & RM=P118-23-00,P118-23-00_0010,1863.5
    1026    1026
River Rch & RM=P118-23-00,P118-23-00_0010,1611.4
    1061    1061
River Rch & RM=P118-23-00,P118-23-00_0010,1443.8
    1121    1121
Boundary for River Rch & Prof#=P118-23-00,P118-23-00_0010, 1
Up Type= 0
Dn Type= 3
Dn Slope= 0.00070
Boundary for River Rch & Prof#=P118-23-00,P118-23-00_0010, 2
Up Type= 0
Dn Type= 3
Dn Slope= 0.00070

--- P118-23-00.f01 (steady flow) ---

Flow Title= FEMA Effective June 2007
Number of Profiles= 4
Profile Names=10PCT_10yr, 2PCT_50yr, 1PCT_100yr, 0.2PCT_500yr
River Rch & RM=P118-23-00,P118-23-00_0010,7654.5
       4       6       7      11
River Rch & RM=P118-23-00,P118-23-00_0010,7426.9
       5       7       8      12
River Rch & RM=P118-23-00,P118-23-00_0010,7372.1
       6       9      10      15
River Rch & RM=P118-23-00,P118-23-00_0010,7237.2
      13      20      23      32
River Rch & RM=P118-23-00,P118-23-00_0010,6786.3
      15      22      26      36
River Rch & RM=P118-23-00,P118-23-00_0010,6717
      20      29      34      48
River Rch & RM=P118-23-00,P118-23-00_0010,6563.4
      26      39      45      63
River Rch & RM=P118-23-00,P118-23-00_0010,6402.4
      28      42      49      68
River Rch & RM=P118-23-00,P118-23-00_0010,6357.2
      57      84      97     137
River Rch & RM=P118-23-00,P118-23-00_0010,5958.6
      97     143     166     234
River Rch & RM=P118-23-00,P118-23-00_0010,5652.9
     262     386     449     632
River Rch & RM=P118-23-00,P118-23-00_0010,5045.3
     269     397     461     648
River Rch & RM=P118-23-00,P118-23-00_0010,4582.1
     273     403     468     658
River Rch & RM=P118-23-00,P118-23-00_0010,4330.8
     281     414     482     677
River Rch & RM=P118-23-00,P118-23-00_0010,3733.5
     289     427     496     697
River Rch & RM=P118-23-00,P118-23-00_0010,3187.4
     515     761     885    1244
River Rch & RM=P118-23-00,P118-23-00_0010,2615.4
     544     804     935    1314
River Rch & RM=P118-23-00,P118-23-00_0010,2245
     561     828     963    1354
River Rch & RM=P118-23-00,P118-23-00_0010,2042.4
     578     854     994    1397
River Rch & RM=P118-23-00,P118-23-00_0010,1863.5
     597     882    1026    1442
River Rch & RM=P118-23-00,P118-23-00_0010,1611.4
     617     912    1061    1491
River Rch & RM=P118-23-00,P118-23-00_0010,1443.8
     653     964    1121    1576
Boundary for River Rch & Prof#=P118-23-00,P118-23-00_0010, 1
Up Type= 0
Dn Type= 3
Dn Slope= 0.00070
Boundary for River Rch & Prof#=P118-23-00,P118-23-00_0010, 2
Up Type= 0
Dn Type= 3
Dn Slope= 0.00070
Boundary for River Rch & Prof#=P118-23-00,P118-23-00_0010, 3
Up Type= 0
Dn Type= 3
Dn Slope= 0.00070
Boundary for River Rch & Prof#=P118-23-00,P118-23-00_0010, 4
Up Type= 0
Dn Type= 3
Dn Slope= 0.00070

--- P118-23-00.g01 (geometry) ---

Geom Title=P118-23-00 June 2007
Version=Version 3.0.1  Mar 2001

River Reach=P118-23-00      ,P118-23-00_0010
Reach XY= 23
      3113797.65     13883752.88      3114072.47     13884131.48
      3114265.46     13884399.25      3114359.25       13884522.
        3115082.       13885488.        3115082.       13885488.
        3115787.       13886450.        3116510.       13887440.
        3116510.       13887440.       3116775.5       13887786.
        3117227.       13888422.      3117255.25       13888462.
      3117288.75       13888506.      3117322.25       13888550.
      3117345.25       13888583.      3117364.75       13888605.
      3117373.75       13888619.      3117373.75       13888619.
        3117384.       13888645.       3117399.5       13888672.
       3117490.5       13888793.       3117490.5       13888793.
       3118184.5       13889712.

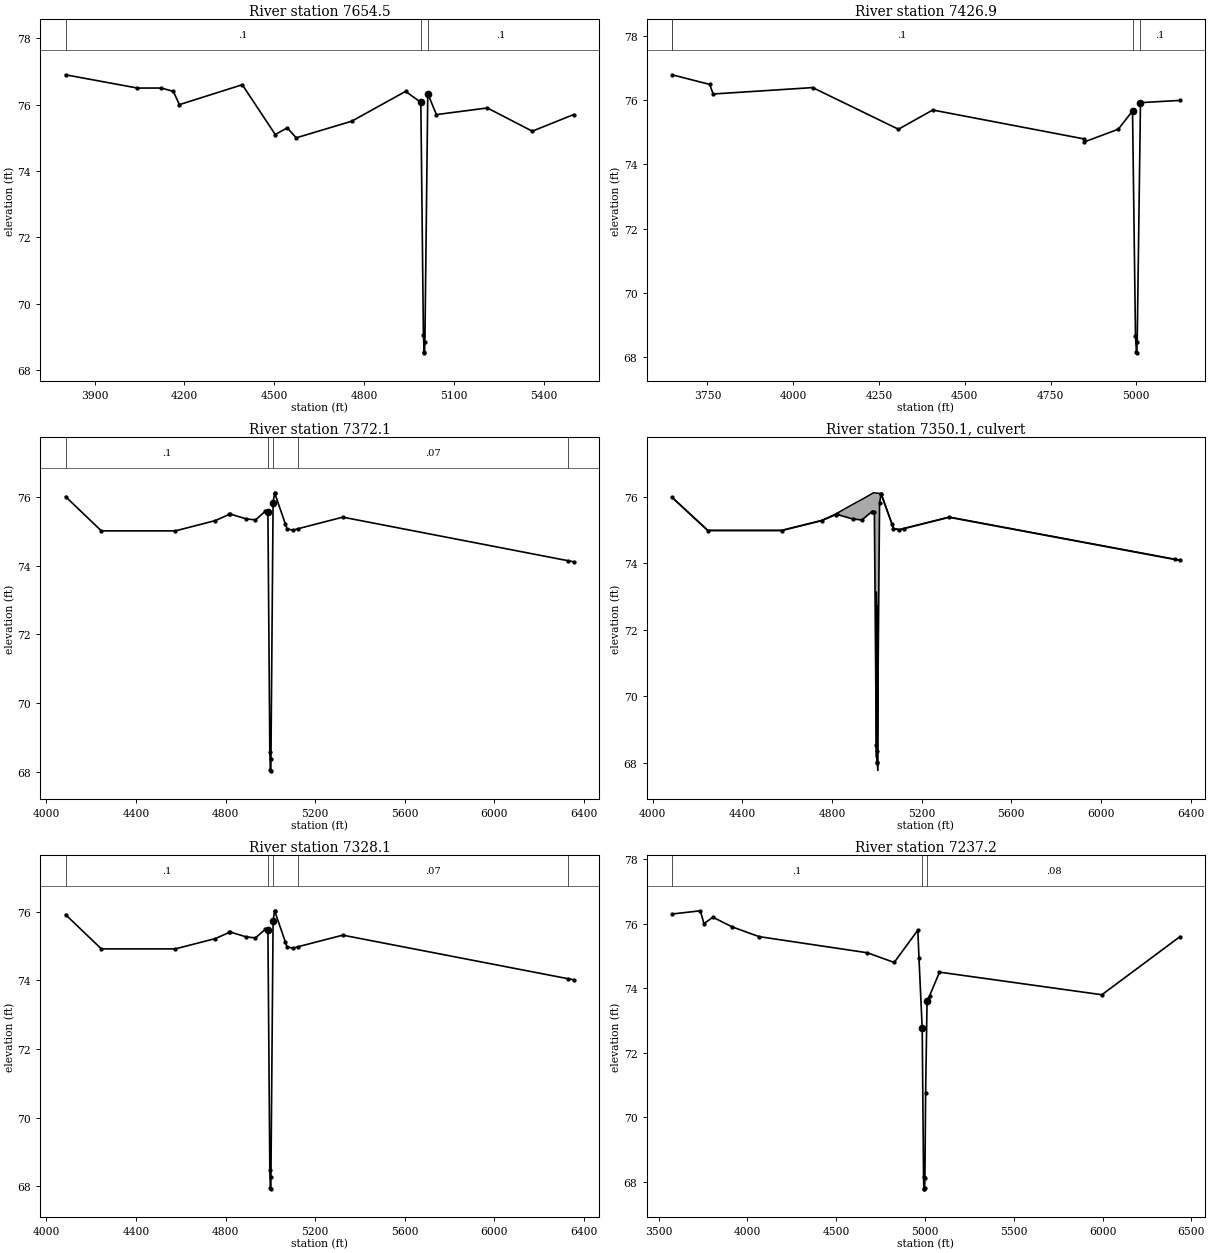
Type RM Length L Ch R = 1 ,7654.5  ,232.6,227.6,124.9
BEGIN DESCRIPTION:
Cross Section 7654.5-Interpolated
END DESCRIPTION:
XS GIS Cut Line= 5
      3112630.91     13883993.25      3113574.32     13883844.28
      3113792.28     13883758.24      3113826.54     13883723.98
      3114260.71       13883579.
#Sta/Elev= 21
    3803    76.9    4043    76.5    4123    76.5    4163    76.4    4183      76
    4393    76.6    4503    75.1    4543    75.3    4573      75  4758.1    75.5
  4938.1    76.4  4988.9   76.07  4997.5   69.06  5000.3   68.55  5000.8   68.52
  5002.5   68.86  5012.1   76.33  5040.9    75.7  5210.9    75.9  5360.9    75.2
  5498.6    75.7
#Mann= 3 , 1 , 0
    3803      .1       0  4988.9     .04       0  5012.1      .1       0
Bank Sta=4988.9,5012.1
XS Rating Curve= 0
Exp/Cntr=.3,.1

Type RM Length L Ch R = 1 ,7426.9  ,58.2,54.8,21
BEGIN DESCRIPTION:
Cross Section 7426.9-Interpolated
END DESCRIPTION:
XS GIS Cut Line= 3
      3112628.63     13884152.32      3113824.65     13884046.34
      3114020.26     13883845.96
#Sta/Elev= 16
  3646.6    76.8  3756.6    76.5  3766.6    76.2  4056.6    76.4  4306.6    75.1
  4406.6    75.7  4846.6    74.8  4847.3    74.7  4947.3    75.1  4988.9   75.67
  4997.5   68.66  5000.3   68.15  5000.8   68.12  5002.5   68.46  5012.1   75.93
  5127.3      76
#Mann= 4 , 1 , 0
  3646.6      .2       0  3646.6      .1       0  4988.9     .04       0
  5012.1      .1       0
Bank Sta=4988.9,5012.1
XS Rating Curve= 0
Exp/Cntr=.5,.3

Type RM Length L Ch R = 1 ,7372.1  ,44,44,44
BEGIN DESCRIPTION:
Upstream Section of Bridge/Culvert/Weir
END DESCRIPTION:
XS GIS Cut Line= 5
      3113089.33      13884153.4      3113846.86     13884081.33
      3113973.41     13883976.08       3114189.2     13883758.06
      3115224.26     13883748.82
#Sta/Elev= 25
  4085.6   76.01  4245.6   75.01  4575.6   75.01  4754.4   75.31  4816.5   75.49
  4821.1    75.5  4891.9   75.36  4933.3   75.33  4977.3   75.58  4984.7   75.57
  4988.9   75.57  4997.5   68.56  5000.3   68.05  5000.8   68.02  5002.5   68.36
  5012.1   75.83  5018.8   76.12  5018.9   76.12  5067.4    75.2  5074.1   75.07
    5101   75.03  5121.7   75.07    5323   75.41  6329.2   74.14    6353   74.11
#Mann= 5 , 1 , 0
  4085.6      .1       0  4988.9     .04       0  5012.1      .1       0
  5121.7     .07       0  6329.2      .2       0
#XS Ineff= 2 , 0
       0    4979    74.8    5022       0      74
Permanent Ineff=
       F       F
Bank Sta=4988.9,5012.1
XS Rating Curve= 0
Exp/Cntr=.5,.3

Type RM Length L Ch R = 2 ,7350.1  ,,,
BEGIN DESCRIPTION:
MELROSE PARK ACCESS ROAD
Structure ID: P83-8,,,,
END DESCRIPTION:
Bridge Culvert--1,0,-1,-1, 0
Deck Dist Width WeirC Skew NumUp NumDn MinLoCord MaxHiCord MaxSubmerge Is_Ogee
10,24,3,0, 25, 25, , , .95, 0, 1,1,,
  4085.6  4245.6  4575.6  4754.4  4816.5  4821.1  4891.9  4933.3  4977.3  4984.7
  4988.9  4997.5  5000.3  5000.8  5002.5  5012.1  5018.8  5018.9  5067.4  5074.1
    5101  5121.7    5323  6329.2    6353
      76      75      75    75.3   75.49   75.51   75.78   75.93    76.1   76.13
   76.13   76.12   76.12   76.12   76.12   76.11   76.11   76.11    75.2   75.06
   75.02   75.06    75.4   74.13    74.1
   75.99   74.99   74.99   75.29   75.47   75.48   75.34   75.31   75.56   75.55
   75.55   68.54   68.03      68   68.34   75.81    76.1    76.1   75.18   75.05
   75.01   75.05   75.39   74.12   74.09
  4085.6  4245.6  4575.6  4754.4  4816.5  4821.1  4891.9  4933.3  4977.3  4984.7
  4988.9  4997.5  5000.3  5000.8  5002.5  5012.1  5018.8  5018.9  5067.4  5074.1
    5101  5121.7    5323  6329.2    6353
      76      75      75    75.3   75.49   75.51   75.78   75.93    76.1   76.13
   76.13   76.12   76.12   76.12   76.12   76.11   76.11   76.11    75.2   75.06
   75.02   75.06    75.4   74.13    74.1
   75.94   74.94   74.94   75.24   75.42   75.43   75.29   75.26   75.51    75.5
    75.5   68.49   67.98   67.95   68.29   75.76   76.05   76.05   75.13      75
   74.96      75   75.34   74.07   74.04
BR Coef= 1 , 0 , 0 ,1.25, 0 ,,,.8,-1,2,0,
WSPro=,,,, 1 ,,,, 0 ,,,, 0 ,,,,-1 ,-1 ,-1 , 0 , 0 , 0 , 0 , 0
Culvert=1,5,,24,.015,.5,1,1,3,68.15,4998,67.94,4998,Culvert #1  , 0 ,10
Culvert Bottom n=.015
Culvert=1,5,,24,.015,.5,1,1,3,67.75,5003.7,67.64,5003.7,Culvert #2  , 0 ,10
Culvert Bottom n=.015
BR U #Sta/Elev= 25
  4085.6   75.99  4245.6   74.99  4575.6   74.99  4754.4   75.29  4816.5   75.47
  4821.1   75.48  4891.9   75.34  4933.3   75.31  4977.3   75.56  4984.7   75.55
  4988.9   75.55  4997.5   68.54  5000.3   68.03  5000.8      68  5002.5   68.34
  5012.1   75.81  5018.8    76.1  5018.9    76.1  5067.4   75.18  5074.1   75.05
    5101   75.01  5121.7   75.05    5323   75.39  6329.2   74.12    6353   74.09
BR U #Mann= 5
  4085.6      .1  4988.9     .04  5012.1      .1  5121.7     .07  6329.2      .2
BR U Banks=4988.9,5012.1
BR D #Sta/Elev= 25
  4085.6   75.94  4245.6   74.94  4575.6   74.94  4754.4   75.24  4816.5   75.42
  4821.1   75.43  4891.9   75.29  4933.3   75.26  4977.3   75.51  4984.7    75.5
  4988.9    75.5  4997.5   68.49  5000.3   67.98  5000.8   67.95  5002.5   68.29
  5012.1   75.76  5018.8   76.05  5018.9   76.05  5067.4   75.13  5074.1      75
    5101   74.96  5121.7      75    5323   75.34  6329.2   74.07    6353   74.04
BR D #Mann= 5
  4085.6      .1  4988.9     .04  5012.1      .1  5121.7     .07  6329.2      .2
BR D Banks=4988.9,5012.1
BC Design=,, 0 ,, 0 ,,,,,,

Type RM Length L Ch R = 1 ,7328.1  ,90.9,90.9,90.9
BEGIN DESCRIPTION:
Downstream Section of Bridge/Culvert/Weir
END DESCRIPTION:
XS GIS Cut Line= 5
      3113115.18     13884189.01       3113872.7     13884116.93
      3113999.25     13884011.68      3114215.04     13883793.66
       3115250.1     13883784.43
#Sta/Elev= 25
  4085.6   75.92  4245.6   74.92  4575.6   74.92  4754.4   75.22  4816.5    75.4
  4821.1   75.41  4891.9   75.27  4933.3   75.24  4977.3   75.49  4984.7   75.48
  4988.9   75.48  4997.5   68.47  5000.3   67.96  5000.8   67.93  5002.5   68.27
  5012.1   75.74  5018.8   76.03  5018.9   76.03  5067.4   75.11  5074.1   74.98
    5101   74.94  5121.7   74.98    5323   75.32  6329.2   74.05    6353   74.02
#Mann= 5 , 1 , 0
  4085.6      .1       0  4988.9     .04       0  5012.1      .1       0
  5121.7     .07       0  6329.2      .2       0
#XS Ineff= 2 , 0
       0    4979    74.6    5022       0      74
Permanent Ineff=
       F       F
Bank Sta=4988.9,5012.1
XS Rating Curve= 0
Exp/Cntr=.5,.3

Type RM Length L Ch R = 1 ,7237.2  ,441.9,450.9,747.8
BEGIN DESCRIPTION:
Cross Section 7237.2
END DESCRIPTION:
XS GIS Cut Line= 6
       3112648.7     13884323.58      3113823.05     13884195.45
      3113999.29     13884116.54      3114112.58     13884048.87
      3114281.52     13883886.54      3115401.19     13883859.29
#Sta/Elev= 23
  3574.9    76.3  3734.9    76.4  3754.9      76  3804.9    76.2  3914.9    75.9
  4064.9    75.6  4674.9    75.1  4826.2    74.8  4959.3    75.8  4965.7   74.94
  4983.9   72.76  4991.5   68.17  4993.4   67.79  4995.5   67.79  4997.4   67.83
  4999.2   68.14  5003.2   70.77  5011.2    73.6  5016.9   73.68    5025   73.76
  5081.3    74.5  5995.6    73.8  6435.6    75.6
#Mann= 3 , 1 , 0
  3574.9      .1       0  4983.9     .04       0  5011.2     .08       0
Bank Sta=4983.9,5011.2
XS Rating Curve= 0
Exp/Cntr=.3,.1

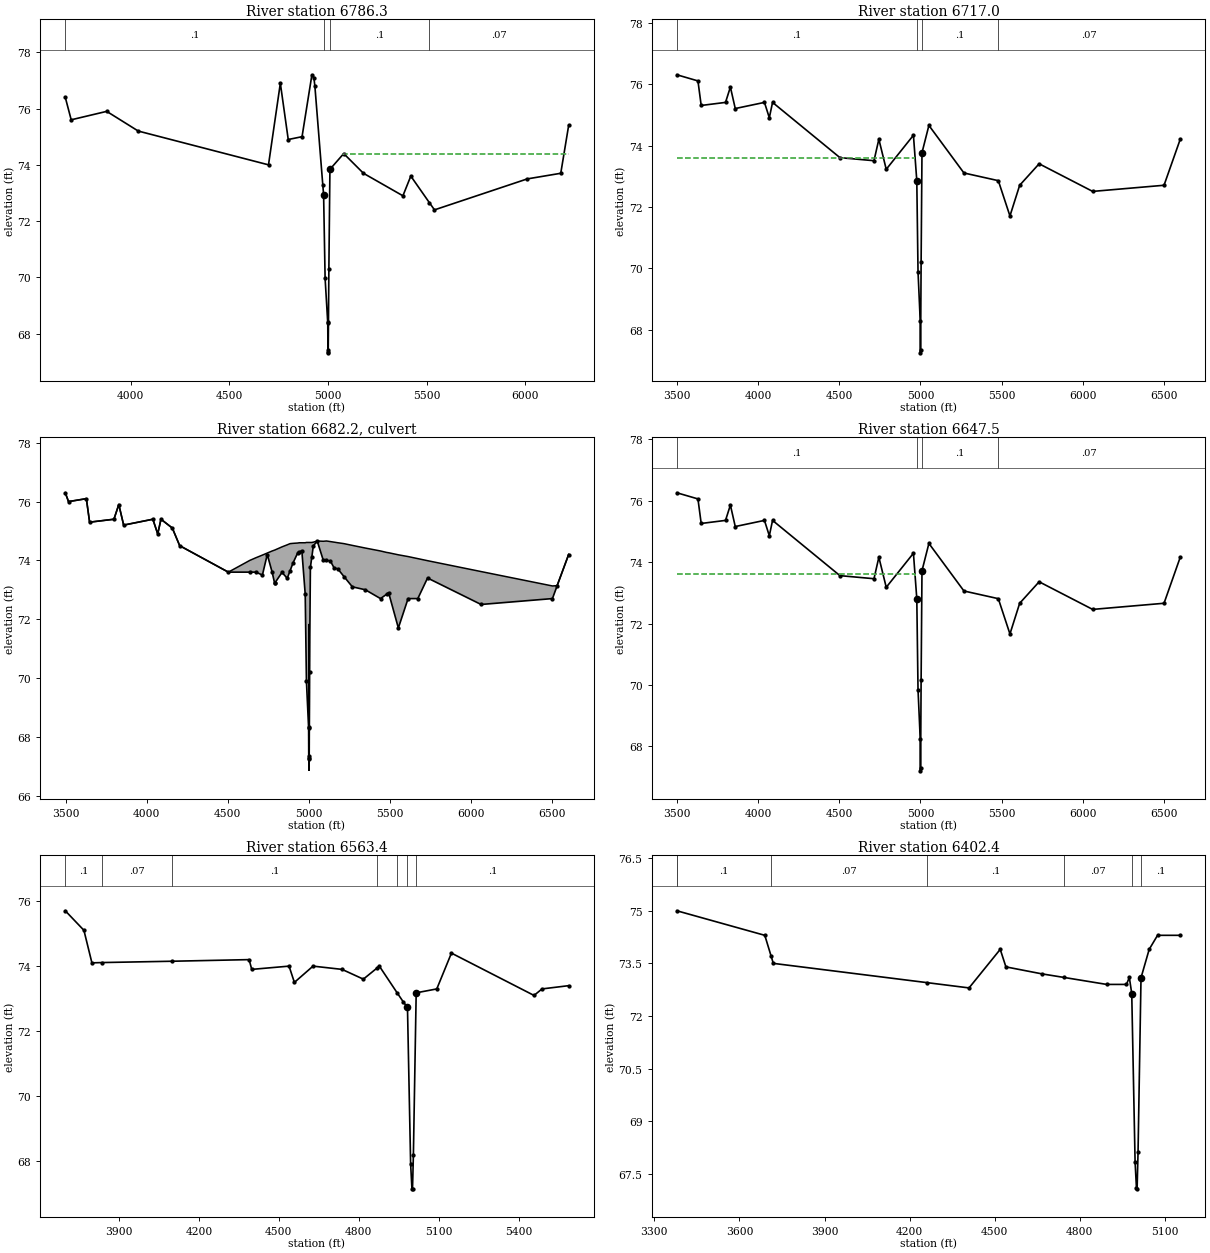
Type RM Length L Ch R = 1 ,6786.3  ,50.3,69.35,68.4
BEGIN DESCRIPTION:
Cross Section 6786.3-Interpolated, SKEW ANGLE OF 35 DEGREES
END DESCRIPTION:
XS GIS Cut Line= 4
      3112976.41     13884424.71      3114240.99     13884455.11
      3114377.25     13884455.11      3115527.08     13884474.58
#Sta/Elev= 30
  3667.9    76.4  3697.9    75.6  3877.9    75.9  4037.9    75.2  4697.9      74
  4757.9    76.9  4797.9    74.9  4867.9      75  4917.9    77.2  4927.9    77.1
  4932.9    76.8  4972.9    73.3  4977.2   72.93 4984.75   69.97 4998.28   68.37
 4999.02   67.34 4999.43   67.32 5000.57   67.41  5001.8   68.42 5003.85   70.29
 5009.18   73.84  5079.1    74.4  5179.1    73.7  5379.1    72.9  5419.1    73.6
  5513.8   72.65  5539.1    72.4  6009.1    73.5  6179.1    73.7  6219.1    75.4
#Mann= 4 , 1 , 0
  3667.9      .1       0  4977.2     .04       0 5009.18      .1       0
  5513.8     .07       0
#XS Ineff= 2 , 0
       0                    5075       0    74.4
Permanent Ineff=
       F       F
Bank Sta=4977.2,5009.18
XS Rating Curve= 0
Exp/Cntr=.5,.3

Type RM Length L Ch R = 1 ,6717.0  ,69.5,69.5,69.5
BEGIN DESCRIPTION:
Upstream Section of Bridge/Culvert/Weir
END DESCRIPTION:
XS GIS Cut Line= 6
      3112844.04     13884462.13      3113212.27     13884462.55
      3113981.64     13884483.41      3114489.83      13884511.3
      3115385.53     13884553.68      3115945.53     13884561.53
#Sta/Elev= 30
  3497.9   76.31  3627.9   76.11  3647.9   75.31  3797.9   75.41  3827.9   75.91
  3857.9   75.21  4037.9   75.41  4067.9   74.91  4087.9   75.41  4503.3   73.61
  4713.3   73.51  4743.3   74.21 4788.77   73.23 4956.46   74.34  4977.2   72.86
 4984.75    69.9 4998.28    68.3 4999.43   67.25 5000.57   67.34 5003.85   70.22
 5009.18   73.77 5051.82   74.66  5267.9   73.11  5479.8   72.86  5551.5   71.71
  5611.5   72.71  5731.5   73.41  6061.5   72.51  6501.5   72.71  6601.5   74.21
#Mann= 4 , 1 , 0
  3497.9      .1       0  4977.2     .04       0 5009.18      .1       0
  5479.8     .07       0
#XS Ineff= 2 , 0
       0    4967    73.6    5019       0    73.1
Permanent Ineff=
       F       F
Bank Sta=4977.2,5009.18
XS Rating Curve= 0
Exp/Cntr=.5,.3

Type RM Length L Ch R = 2 ,6682.2  ,,,
BEGIN DESCRIPTION:
CARBY ROAD, SKEW ANGLE OF 35 DEGREES
Structure ID: P83-7
END DESCRIPTION:
Bridge Culvert--1,0,-1,-1, 0
Deck Dist Width WeirC Skew NumUp NumDn MinLoCord MaxHiCord MaxSubmerge Is_Ogee
10,49.5,3,0, 58, 58, , , .95, 0, 1,1,,
  3497.9  3517.9  3627.9  3647.9  3797.9  3827.9  3857.9  4037.9  4067.9  4087.9
  4157.9  4203.3  4503.3  4635.7  4673.3  4713.3  4743.3  4773.3 4788.69 4788.77
  4834.2  4866.5  4884.1 4902.75 4929.73  4941.6 4956.46  4977.2 4984.75 4998.28
 4999.02 4999.43 5000.57  5001.8 5003.85 5009.18  5017.7 5027.47 5051.82 5088.23
  5108.3 5132.18 5155.72 5178.35  5216.1  5267.9  5347.9  5441.5  5479.8  5491.5
  5551.5  5611.5  5671.5  5731.5  6061.5  6501.5  6530.1  6601.5
    76.3      76    76.1    75.3    75.4    75.9    75.2    75.4    74.9    75.4
    75.1    74.5    73.6      74   74.09   74.18   74.25   74.32   74.35   74.35
   74.46   74.53   74.57   74.58   74.59    74.6    74.6    74.6   74.61   74.61
   74.61   74.61   74.61   74.61   74.61   74.61   74.61   74.62   74.66   74.65
   74.66   74.64   74.62    74.6   74.57   74.51   74.42   74.32   74.27   74.26
   74.19   74.13   74.06   73.99   73.62   73.13   73.14    74.2
    76.3      76    76.1    75.3    75.4    75.9    75.2    75.4    74.9    75.4
    75.1    74.5    73.6    73.6    73.6    73.5    74.2    73.6   73.22   73.22
   73.59   73.39   73.65   73.92   74.24   74.28   74.33   72.85   69.89   68.29
   67.26   67.24   67.33   68.34   70.21   73.76    74.1    74.5   74.65   74.01
      74   73.98   73.74   73.71   73.45    73.1      73    72.7   72.85    72.9
    71.7    72.7    72.7    73.4    72.5    72.7   73.13    74.2
  3497.9  3517.9  3627.9  3647.9  3797.9  3827.9  3857.9  4037.9  4067.9  4087.9
  4157.9  4203.3  4503.3  4635.7  4673.3  4713.3  4743.3  4773.3 4788.69 4788.77
  4834.2  4866.5  4884.1 4902.75 4929.73  4941.6 4956.46  4977.2 4984.75 4998.28
 4999.02 4999.43 5000.57  5001.8 5003.85 5009.18  5017.7 5027.47 5051.82 5088.23
  5108.3 5132.18 5155.72 5178.35  5216.1  5267.9  5347.9  5441.5  5479.8  5491.5
  5551.5  5611.5  5671.5  5731.5  6061.5  6501.5  6530.1  6601.5
    76.3      76    76.1    75.3    75.4    75.9    75.2    75.4    74.9    75.4
    75.1    74.5    73.6      74   74.09   74.18   74.25   74.32   74.35   74.35
   74.46   74.53   74.57   74.58   74.59    74.6    74.6    74.6   74.61   74.61
   74.61   74.61   74.61   74.61   74.61   74.61   74.61   74.62   74.66   74.65
   74.66   74.64   74.62    74.6   74.57   74.51   74.42   74.32   74.27   74.26
   74.19   74.13   74.06   73.99   73.62   73.13   73.14    74.2
   76.26   75.96   76.06   75.26   75.36   75.86   75.16   75.36   74.86   75.36
   75.06   74.46   73.56   73.56   73.56   73.46   74.16   73.56   73.18   73.18
   73.55   73.35   73.61   73.88    74.2   74.24   74.29   72.81   69.85   68.25
   67.22    67.2   67.29    68.3   70.17   73.72   74.06   74.46   74.61   73.97
   73.96   73.94    73.7   73.67   73.41   73.06   72.96   72.66   72.81   72.86
   71.66   72.66   72.66   73.36   72.46   72.66   73.09   74.16
BR Coef= 1 , 0 , 0 ,1.25, 0 ,,,.8,-1,2,0,
WSPro=,,,, 1 ,,,, 0 ,,,, 0 ,,,,-1 ,-1 ,-1 , 0 , 0 , 0 , 0 , 0
Culvert=1,5,,49.5,.015,.5,1,1,3,66.84,5001.2,66.68,5001.2,Culvert #1  , 0 ,10
Culvert Bottom n=.015
BR U #Sta/Elev= 58
  3497.9    76.3  3517.9      76  3627.9    76.1  3647.9    75.3  3797.9    75.4
  3827.9    75.9  3857.9    75.2  4037.9    75.4  4067.9    74.9  4087.9    75.4
  4157.9    75.1  4203.3    74.5  4503.3    73.6  4635.7    73.6  4673.3    73.6
  4713.3    73.5  4743.3    74.2  4773.3    73.6 4788.69   73.22 4788.77   73.22
  4834.2   73.59  4866.5   73.39  4884.1   73.65 4902.75   73.92 4929.73   74.24
  4941.6   74.28 4956.46   74.33  4977.2   72.85 4984.75   69.89 4998.28   68.29
 4999.02   67.26 4999.43   67.24 5000.57   67.33  5001.8   68.34 5003.85   70.21
 5009.18   73.76  5017.7    74.1 5027.47    74.5 5051.82   74.65 5088.23   74.01
  5108.3      74 5132.18   73.98 5155.72   73.74 5178.35   73.71  5216.1   73.45
  5267.9    73.1  5347.9      73  5441.5    72.7  5479.8   72.85  5491.5    72.9
  5551.5    71.7  5611.5    72.7  5671.5    72.7  5731.5    73.4  6061.5    72.5
  6501.5    72.7  6530.1   73.13  6601.5    74.2
BR U #Mann= 4
  3497.9      .1  4977.2     .04 5009.18      .1  5479.8     .07
BR U Banks=4977.2,5009.18
BR D #Sta/Elev= 58
  3497.9   76.26  3517.9   75.96  3627.9   76.06  3647.9   75.26  3797.9   75.36
  3827.9   75.86  3857.9   75.16  4037.9   75.36  4067.9   74.86  4087.9   75.36
  4157.9   75.06  4203.3   74.46  4503.3   73.56  4635.7   73.56  4673.3   73.56
  4713.3   73.46  4743.3   74.16  4773.3   73.56 4788.69   73.18 4788.77   73.18
  4834.2   73.55  4866.5   73.35  4884.1   73.61 4902.75   73.88 4929.73    74.2
  4941.6   74.24 4956.46   74.29  4977.2   72.81 4984.75   69.85 4998.28   68.25
 4999.02   67.22 4999.43    67.2 5000.57   67.29  5001.8    68.3 5003.85   70.17
 5009.18   73.72  5017.7   74.06 5027.47   74.46 5051.82   74.61 5088.23   73.97
  5108.3   73.96 5132.18   73.94 5155.72    73.7 5178.35   73.67  5216.1   73.41
  5267.9   73.06  5347.9   72.96  5441.5   72.66  5479.8   72.81  5491.5   72.86
  5551.5   71.66  5611.5   72.66  5671.5   72.66  5731.5   73.36  6061.5   72.46
  6501.5   72.66  6530.1   73.09  6601.5   74.16
BR D #Mann= 4
  3497.9      .1  4977.2     .04 5009.18      .1  5479.8     .07
BR D Banks=4977.2,5009.18
BC Design=,, 0 ,, 0 ,,,,,,

Type RM Length L Ch R = 1 ,6647.5  ,84.05,84.05,84.05
BEGIN DESCRIPTION:
Downstream Section of Bridge/Culvert/Weir
END DESCRIPTION:
XS GIS Cut Line= 6
      3112885.67     13884517.77      3113253.91     13884518.19
      3114023.28     13884539.05      3114531.47     13884566.94
      3115427.17     13884609.32      3115987.17     13884617.17
#Sta/Elev= 30
  3497.9   76.26  3627.9   76.06  3647.9   75.26  3797.9   75.36  3827.9   75.86
  3857.9   75.16  4037.9   75.36  4067.9   74.86  4087.9   75.36  4503.3   73.56
  4713.3   73.46  4743.3   74.16 4788.77   73.18 4956.46   74.29  4977.2   72.81
 4984.75   69.85 4998.28   68.25 4999.43    67.2 5000.57   67.29 5003.85   70.17
 5009.18   73.72 5051.82   74.61  5267.9   73.06  5479.8   72.81  5551.5   71.66
  5611.5   72.66  5731.5   73.36  6061.5   72.46  6501.5   72.66  6601.5   74.16
#Mann= 4 , 1 , 0
  3497.9      .1       0  4977.2     .04       0 5009.18      .1       0
  5479.8     .07       0
#XS Ineff= 2 , 0
       0    4967    73.6    5019       0    73.1
Permanent Ineff=
       F       F
Bank Sta=4977.2,5009.18
XS Rating Curve= 0
Exp/Cntr=.5,.3

Type RM Length L Ch R = 1 ,6563.4  ,166.4,161,41.7
BEGIN DESCRIPTION:
Cross Section 6563.4-Interpolated
END DESCRIPTION:
XS GIS Cut Line= 5
      3113142.98     13884702.29      3114180.84     13884656.24
      3114435.56     13884634.65      3114586.67     13884600.12
      3115026.56     13884609.02
#Sta/Elev= 27
  3698.5    75.7  3768.5    75.1  3798.5    74.1  3837.6   74.11  4098.6   74.15
  4388.5    74.2  4398.5    73.9  4538.5      74  4558.5    73.5  4628.5      74
  4737.4    73.9  4817.4    73.6  4868.5   73.94  4877.4      74  4944.2   73.18
  4967.4    72.9    4983   72.73  4994.8   67.93  4999.7   67.17  5001.9   67.16
  5005.2    68.2  5015.7   73.18    5093    73.3    5148    74.4    5458    73.1
    5488    73.3    5588    73.4
#Mann= 7 , 1 , 0
  3698.5      .1       0  3837.6     .07       0  4098.6      .1       0
  4868.5     .07       0  4944.2      .1       0    4983     .04       0
  5015.7      .1       0
Bank Sta=4983,5015.7
XS Rating Curve= 0
Exp/Cntr=.3,.1

Type RM Length L Ch R = 1 ,6402.4  ,50.7,45.2,41.3
BEGIN DESCRIPTION:
Cross Section 6402.4-Interpolated
END DESCRIPTION:
XS GIS Cut Line= 5
      3112938.99      13884833.6      3114225.85     13884871.45
      3114445.37     13884810.89      3114604.34     13884727.62
      3114680.01     13884701.67
#Sta/Elev= 22
  3379.4      75  3689.4    74.3  3711.2   73.72  3719.4    73.5  4262.1   72.95
  4409.4    72.8  4519.4    73.9  4539.4    73.4  4666.8    73.2  4743.3    73.1
  4894.5    72.9  4964.5    72.9  4974.5    73.1    4983   72.64  4994.8   67.84
  4999.7   67.08  5001.9   67.07  5005.2   68.11  5015.7   73.09  5044.5    73.9
    5074    74.3    5154    74.3
#Mann= 7 , 1 , 0
  3379.4      .2       0  3379.4      .1       0  3711.2     .07       0
  4262.1      .1       0  4743.3     .07       0    4983     .04       0
  5015.7      .1       0
Bank Sta=4983,5015.7
XS Rating Curve= 0
Exp/Cntr=.5,.3

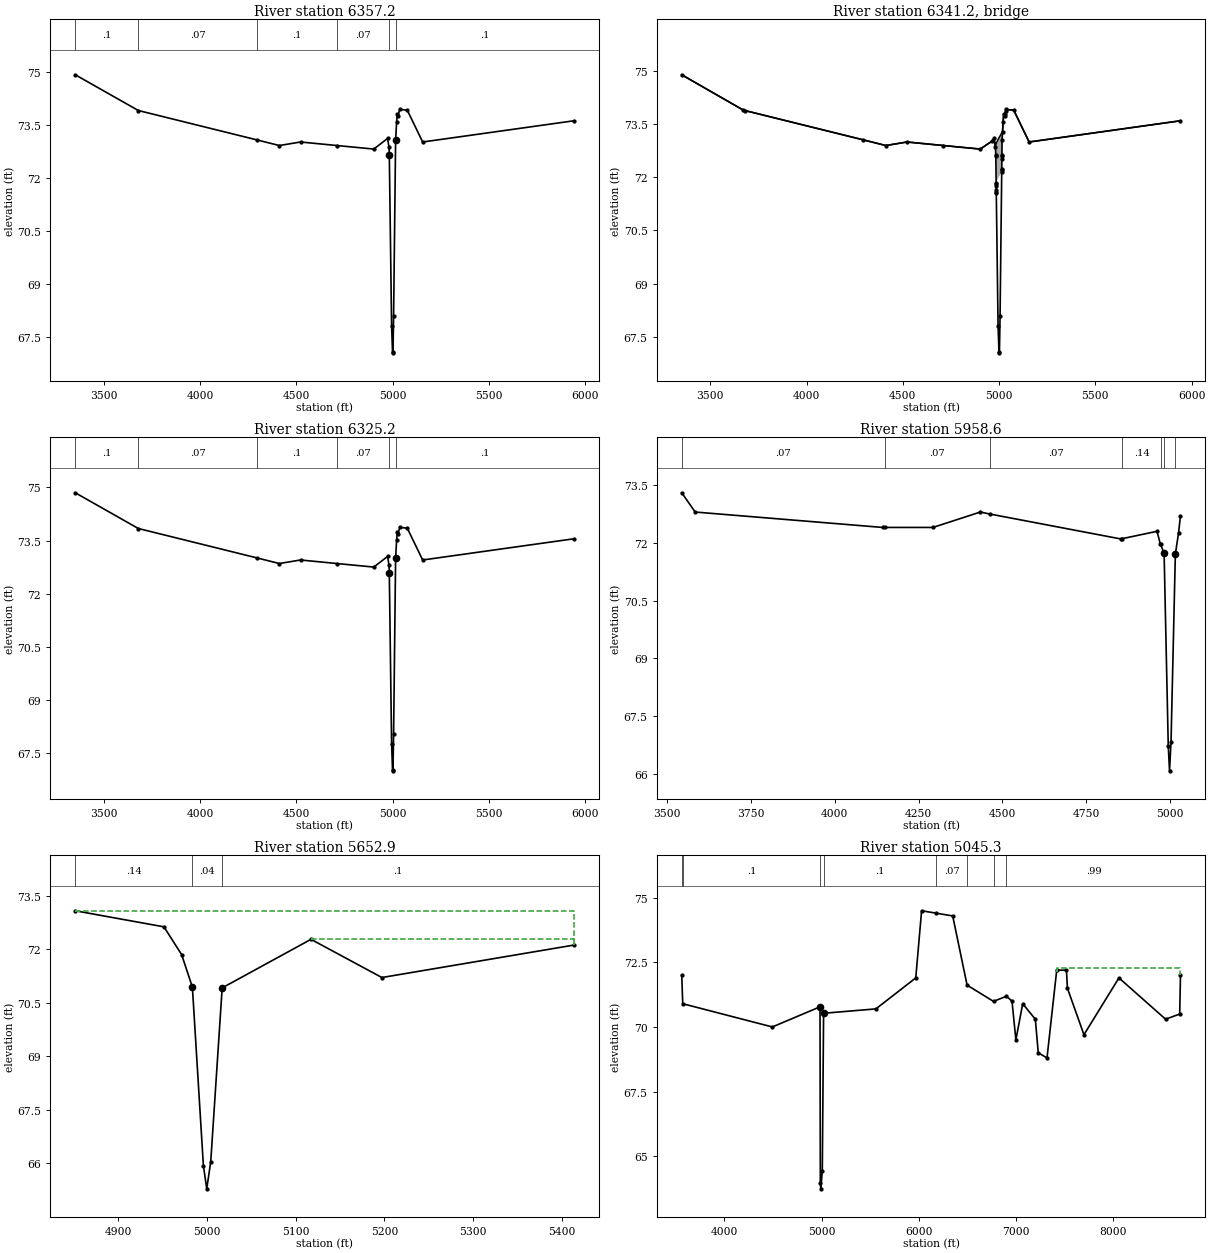
Type RM Length L Ch R = 1 ,6357.2  ,32,32,32
BEGIN DESCRIPTION:
Upstream Section of Bridge/Culvert/Weir
END DESCRIPTION:
XS GIS Cut Line= 6
       3112939.8     13884900.05      3114235.71     13884911.91
      3114478.92     13884849.66      3114629.32     13884760.44
      3114916.58     13884689.09      3115488.66     13884711.56
#Sta/Elev= 22
  3351.9   74.91  3679.4    73.9  4294.8   73.07  4411.9   72.91  4521.9   73.01
  4710.7   72.91  4902.3   72.81  4973.8   73.11  4981.5   72.86  4982.9   72.64
  4994.8   67.82  4999.7   67.06  5001.9   67.05  5005.2   68.09  5015.7   73.07
  5020.9   73.57  5024.3   73.81  5028.7   73.75  5036.6   73.93  5076.2   73.91
  5156.2   73.01  5942.3   73.61
#Mann= 6 , 1 , 0
  3351.9      .1       0  3679.4     .07       0  4294.8      .1       0
  4710.7     .07       0  4982.9     .04       0  5015.7      .1       0
#XS Ineff= 2 , 0
       0    4975    72.8    5024       0   72.59
Permanent Ineff=
       F       F
Bank Sta=4982.9,5015.7
XS Rating Curve= 0
Exp/Cntr=.5,.3

Type RM Length L Ch R = 3 ,6341.2  ,,,
BEGIN DESCRIPTION:
FOOTBRIDGE 4
Structure ID: P83-7A,,,,
END DESCRIPTION:
Bridge Culvert--1,0,-1,-1, 0
Deck Dist Width WeirC Skew NumUp NumDn MinLoCord MaxHiCord MaxSubmerge Is_Ogee
10,12,2.6,0, 40, 40, , , .95, 0, 1,1,,
  3351.9  3671.9  3679.4  4294.8  4411.9  4521.9  4710.7  4902.3  4962.2  4973.8
  4981.5  4982.9    4983 4984.91    4985  4985.1 4985.39  4985.5 4985.61  4994.8
  4999.7  5001.9  5005.2  5013.8 5013.89    5014 5014.59  5014.7 5014.81  5015.7
    5018  5020.9  5024.3  5028.7  5032.8  5035.5  5036.6  5076.2  5156.2  5942.3
    74.9    73.9   73.89   73.06    72.9      73    72.9    72.8   73.02    73.1
   72.85   72.95   72.95   72.97   72.97   72.97   72.97   72.97   72.97   73.07
   73.12   73.14   73.17   73.26   73.26   73.26   73.27   73.27   73.27   73.28
    73.3   73.56    73.8   73.74   73.79   73.89   73.92    73.9      73    73.6
    74.9    73.9   73.89   73.06    72.9      73    72.9    72.8   73.02    73.1
   72.85   72.63   72.61   71.83   71.87   71.87   71.87   71.87   71.87   71.97
   72.02   72.04   72.07   72.16    72.2   72.25   72.53   72.59   72.64   73.06
   73.28   73.56    73.8   73.74   73.79   73.89   73.92    73.9      73    73.6
  3351.9  3671.9  3679.4  4294.8  4411.9  4521.9  4710.7  4902.3  4962.2  4973.8
  4981.5  4982.9    4983 4984.91    4985  4985.1 4985.39  4985.5 4985.61  4994.8
  4999.7  5001.9  5005.2  5013.8 5013.89    5014 5014.59  5014.7 5014.81  5015.7
    5018  5020.9  5024.3  5028.7  5032.8  5035.5  5036.6  5076.2  5156.2  5942.3
    74.9    73.9   73.89   73.06    72.9      73    72.9    72.8   73.02    73.1
   72.85   72.95   72.95   72.97   72.97   72.97   72.97   72.97   72.97   73.07
   73.12   73.14   73.17   73.26   73.26   73.26   73.27   73.27   73.27   73.28
    73.3   73.56    73.8   73.74   73.79   73.89   73.92    73.9      73    73.6
   74.87   73.87   73.86   73.03   72.87   72.97   72.87   72.77   72.99   73.07
   72.82    72.6   72.58    71.8   71.84   71.84   71.84   71.84   71.84   71.94
   71.99   72.01   72.04   72.13   72.17   72.22    72.5   72.56   72.61   73.03
   73.25   73.53   73.77   73.71   73.76   73.86   73.89   73.87   72.97   73.57
BR Coef= 1 , 1 , 0 ,1.25, 0 ,,,.8,0,2,0,
WSPro=,,,, 1 ,,,, 0 ,,,, 0 ,,,,-1 ,-1 ,-1 , 0 , 0 , 0 , 0 , 0
BR U #Sta/Elev= 40
  3351.9    74.9  3671.9    73.9  3679.4   73.89  4294.8   73.06  4411.9    72.9
  4521.9      73  4710.7    72.9  4902.3    72.8  4962.2   73.02  4973.8    73.1
  4981.5   72.85  4982.9   72.63    4983   72.61 4984.91   71.83    4985    71.8
  4985.1   71.76 4985.39   71.64  4985.5   71.59 4985.61   71.55  4994.8   67.81
  4999.7   67.05  5001.9   67.04  5005.2   68.08  5013.8   72.16 5013.89    72.2
    5014   72.25 5014.59   72.53  5014.7   72.59 5014.81   72.64  5015.7   73.06
    5018   73.28  5020.9   73.56  5024.3    73.8  5028.7   73.74  5032.8   73.79
  5035.5   73.89  5036.6   73.92  5076.2    73.9  5156.2      73  5942.3    73.6
BR U #Mann= 6
  3351.9      .1  3679.4     .07  4294.8      .1  4710.7     .07  4982.9     .04
  5015.7      .1
BR U Banks=4982.9,5015.7
BR D #Sta/Elev= 40
  3351.9   74.87  3671.9   73.87  3679.4   73.86  4294.8   73.03  4411.9   72.87
  4521.9   72.97  4710.7   72.87  4902.3   72.77  4962.2   72.99  4973.8   73.07
  4981.5   72.82  4982.9    72.6    4983   72.58 4984.91    71.8    4985   71.77
  4985.1   71.73 4985.39   71.61  4985.5   71.56 4985.61   71.52  4994.8   67.78
  4999.7   67.02  5001.9   67.01  5005.2   68.05  5013.8   72.13 5013.89   72.17
    5014   72.22 5014.59    72.5  5014.7   72.56 5014.81   72.61  5015.7   73.03
    5018   73.25  5020.9   73.53  5024.3   73.77  5028.7   73.71  5032.8   73.76
  5035.5   73.86  5036.6   73.89  5076.2   73.87  5156.2   72.97  5942.3   73.57
BR D #Mann= 6
  3351.9      .1  3679.4     .07  4294.8      .1  4710.7     .07  4982.9     .04
  5015.7      .1
BR D Banks=4982.9,5015.7
BC Design=,, 0 ,, 0 ,,,,,,

Type RM Length L Ch R = 1 ,6325.2  ,366.6,366.6,366.6
BEGIN DESCRIPTION:
Downstream Section of Bridge/Culvert/Weir
END DESCRIPTION:
XS GIS Cut Line= 6
      3112958.97     13884925.67      3114254.89     13884937.53
       3114498.1     13884875.28       3114648.5     13884786.06
      3114935.76     13884714.71      3115507.83     13884737.19
#Sta/Elev= 22
  3351.9   74.85  3679.4   73.84  4294.8   73.01  4411.9   72.85  4521.9   72.95
  4710.7   72.85  4902.3   72.75  4973.8   73.05  4981.5    72.8  4982.9   72.58
  4994.8   67.76  4999.7      67  5001.9   66.99  5005.2   68.03  5015.7   73.01
  5020.9   73.51  5024.3   73.75  5028.7   73.69  5036.6   73.87  5076.2   73.85
  5156.2   72.95  5942.3   73.55
#Mann= 6 , 1 , 0
  3351.9      .1       0  3679.4     .07       0  4294.8      .1       0
  4710.7     .07       0  4982.9     .04       0  5015.7      .1       0
#XS Ineff= 2 , 0
       0    4975    72.8    5024       0   72.56
Permanent Ineff=
       F       F
Bank Sta=4982.9,5015.7
XS Rating Curve= 0
Exp/Cntr=.5,.3

Type RM Length L Ch R = 1 ,5958.6  ,366.8,305.7,141.9
BEGIN DESCRIPTION:
Cross Section 5958.6
END DESCRIPTION:
XS GIS Cut Line= 5
      3113352.72     13885097.58      3114244.31     13885116.58
      3114690.63     13885146.79      3114787.95      13885123.3
       3114835.1     13885106.49
#Sta/Elev= 19
    3543    73.3    3583    72.8    4143    72.4  4150.2    72.4    4293    72.4
  4434.8    72.8    4462   72.75  4854.8    72.1  4859.1   72.11  4962.2    72.3
  4972.1   71.97  4972.7   71.96  4983.4   71.73  4995.8   66.73  4999.6   66.08
  5004.1   66.84    5017   71.71  5026.4   72.25  5032.3    72.7
#Mann= 7 , 1 , 0
    3543     .07       0  4150.2     .07       0    4462     .07       0
  4859.1     .14       0  4972.7      .1       0  4983.4     .04       0
    5017      .1       0
Bank Sta=4983.4,5017
XS Rating Curve= 0
Exp/Cntr=.3,.1

Type RM Length L Ch R = 1 ,5652.9  ,528.4,607.6,315.1
BEGIN DESCRIPTION:
Cross Section 5652.9-Interpolated
END DESCRIPTION:
XS GIS Cut Line= 4
      3114873.14     13885456.77      3115078.13     13885287.43
      3115318.83     13885198.28      3115358.84     13885199.56
#Sta/Elev= 11
  4851.3   73.08  4951.3   72.63  4971.3   71.85  4983.4   70.94  4995.8   65.94
  4999.6   65.29  5004.1   66.05    5017   70.92  5117.2   72.28  5197.2   71.21
  5413.9   72.12
#Mann= 3 , 1 , 0
  4851.3     .14       0  4983.4     .04       0    5017      .1       0
#XS Ineff= 2 , 0
       0  4851.3   73.08  5117.2       0   72.28
Permanent Ineff=
       F       F
Bank Sta=4983.4,5017
XS Rating Curve= 0
Exp/Cntr=.3,.1

Type RM Length L Ch R = 1 ,5045.3  ,59.4,108.8,199.2
BEGIN DESCRIPTION:
Cross Section 5045.3-Interpolated
END DESCRIPTION:
XS GIS Cut Line= 6
      3113949.43     13885943.57      3114879.88     13885992.53
      3115267.45     13885931.97      3115430.96     13885768.47
      3115800.37     13885526.23      3118933.25     13885498.91
#Sta/Elev= 30
  3561.8      72  3571.8    70.9  4493.6      70 4983.91   70.78 4987.13   63.95
 4992.11   63.73 5007.51   64.43 5020.76   70.53  5558.8    70.7  5968.8    71.9
  6028.8    74.5  6175.6   74.41  6348.8    74.3  6496.7   71.62  6768.6   70.99
  6901.8   71.19  6958.8      71  6998.8    69.5  7068.8    70.9  7198.8    70.3
  7228.8      69  7318.8    68.8  7418.8    72.2  7518.8    72.2  7528.8    71.5
  7698.8    69.7  8058.8    71.9  8538.8    70.3  8683.7    70.5  8691.8      72
#Mann= 8 , 1 , 0
  3561.8      .2       0  3571.8      .1       0 4983.91     .04       0
 5020.76      .1       0  6175.6     .07       0  6496.7     .14       0
  6768.6      .1       0  6901.8     .99       0
#XS Ineff= 2 , 0
       0                    7417       0    72.3
Permanent Ineff=
       F       F
Bank Sta=4983.91,5020.76
XS Rating Curve= 0
Exp/Cntr=.5,.3