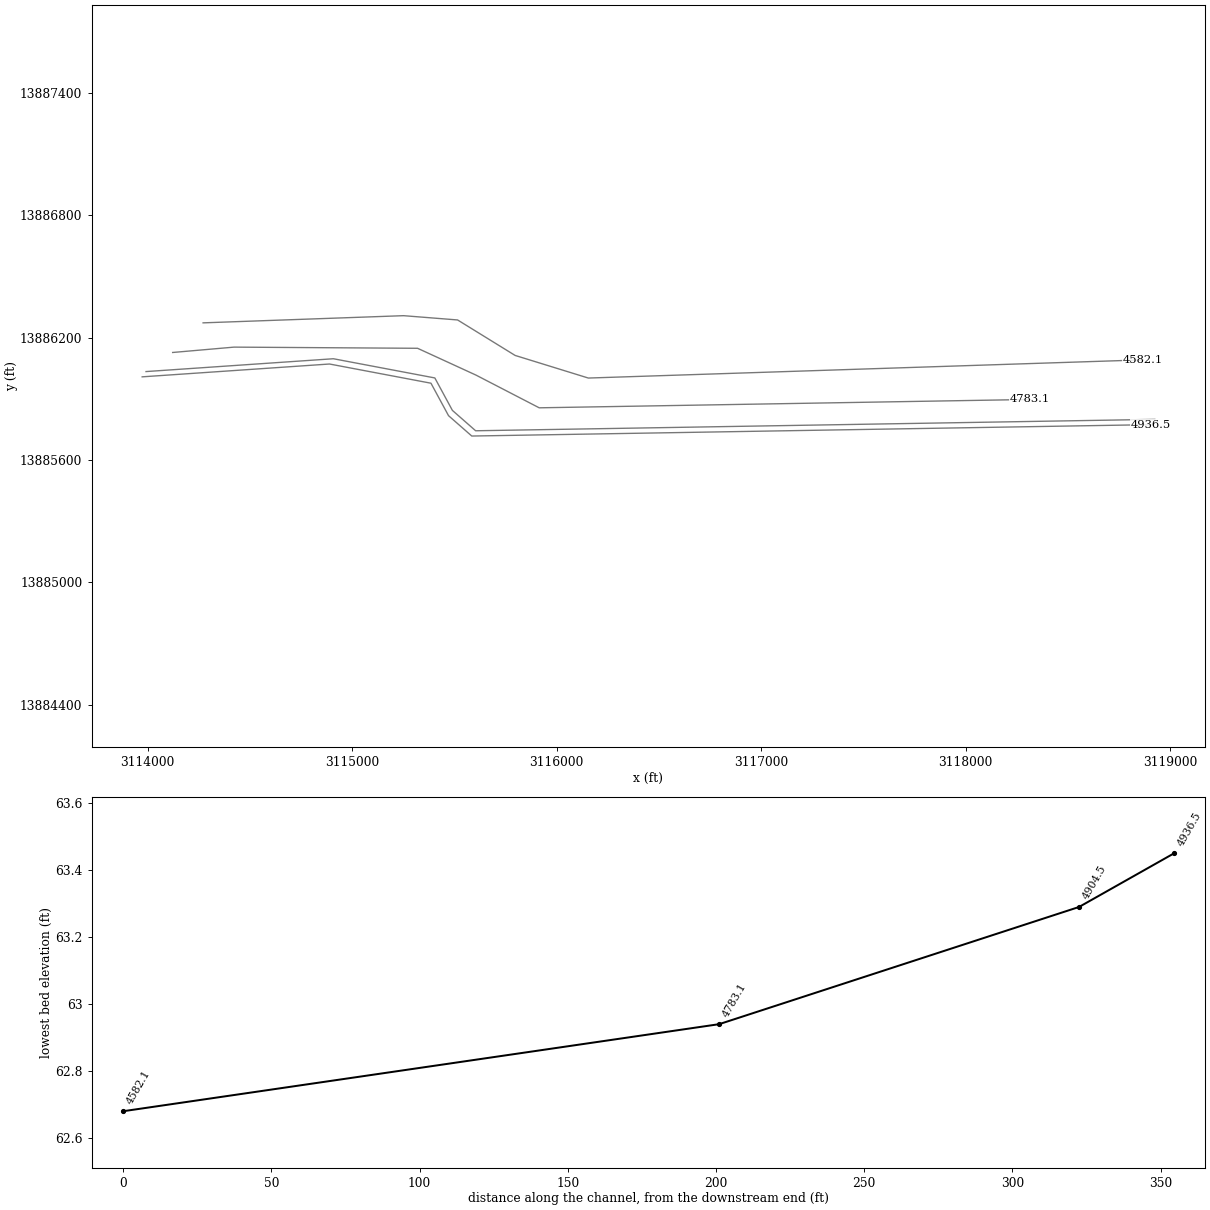
HEC-RAS study P118-23-00.PRJ: P118-23-00

--- P118-23-00.g01 (geometry) --- (continued)

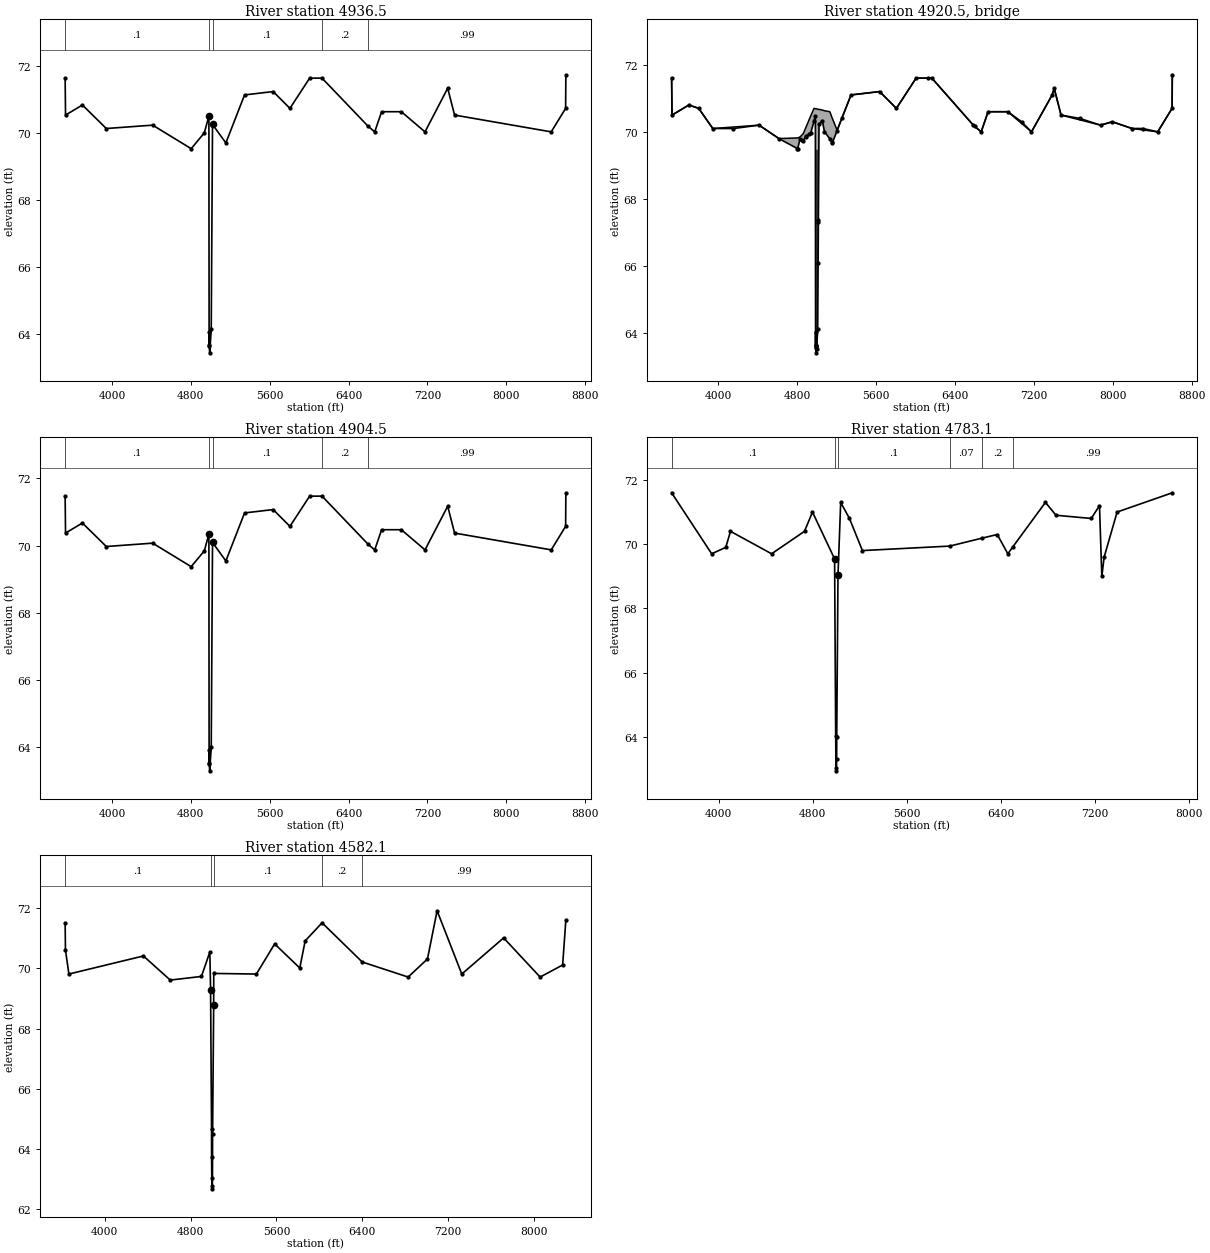
Type RM Length L Ch R = 1 ,4936.5  ,32,32,32
BEGIN DESCRIPTION:
Upstream Section of Bridge/Culvert/Weir
END DESCRIPTION:
XS GIS Cut Line= 6
      3113972.79     13886007.21      3114888.99     13886070.09
      3115385.25     13885975.99      3115471.15     13885816.95
       3115584.8     13885717.12      3118906.44     13885772.95
#Sta/Elev= 30
    3526   71.63    3530   70.53    3701   70.83  3943.4   70.13  4413.4   70.23
  4804.3   69.53 4937.42      70 4983.91    70.5 4986.14   63.65  4986.9   64.08
 4987.13   63.67 4992.11   63.45 5007.51   64.15 5020.76   70.25 5156.03    69.7
  5345.6   71.13  5635.6   71.23  5805.6   70.73  6005.6   71.63  6131.2   71.63
    6601   70.19  6665.6   70.03  6735.6   70.63  6935.6   70.63  7175.6   70.03
  7405.6   71.33  7475.6   70.53  8455.6   70.03  8601.6   70.73    8604   71.73
#Mann= 5 , 1 , 0
    3526      .1       0 4983.91     .04       0 5020.76      .1       0
  6131.2      .2       0    6601     .99       0
#XS Ineff= 2 , 0
       0    4977    69.8    5025       0    70.2
Permanent Ineff=
       F       F
Bank Sta=4983.91,5020.76
XS Rating Curve= 0
Exp/Cntr=.5,.3

Type RM Length L Ch R = 3 ,4920.5  ,,,
BEGIN DESCRIPTION:
FOOTBRIDGE 3, SKEW ANGLE OF 40 DEGREES
Structure ID: P83-6A,,,,
END DESCRIPTION:
Bridge Culvert--1,0,-1,-1, 0
Deck Dist Width WeirC Skew NumUp NumDn MinLoCord MaxHiCord MaxSubmerge Is_Ogee
10,12,2.6,0, 45, 45, , , .95, 0, 1,1,,
    3526    3530    3701    3801  3943.4  4413.4  4614.3  4804.3 4829.34 4861.81
 4937.42  4970.3 4983.91 4986.14  4986.9 4987.13  4987.3 4987.39 5014.48 5014.59
 5020.76 5054.46 5075.99  5130.8 5156.03  5204.6  5345.6  5635.6  5805.6  6005.6
  6165.6  6585.6  6665.6  6735.6  6935.6  7175.6  7385.6  7405.6  7475.6  7875.6
  7995.6  8195.6  8455.6  8601.6    8604
    71.6    70.5    70.8    70.7    70.1    70.2    69.8   69.82   69.85   69.95
   70.48    70.7   70.69   70.69   70.69   70.69   70.69   70.69   70.67   70.67
   70.67   70.65   70.63    70.6    70.4   70.05    71.1    71.2    70.7    71.6
    71.6    70.2      70    70.6    70.6      70    71.1    71.3    70.5    70.2
    70.3    70.1      70    70.7    71.7
    71.6    70.5    70.8    70.7    70.1    70.2    69.8    69.5   69.79   69.74
   69.97   70.32   70.47   63.62   64.05   63.64   63.63   69.49   69.47   67.38
   70.22   70.33   70.01   69.79   69.67   70.04    71.1    71.2    70.7    71.6
    71.6    70.2      70    70.6    70.6      70    71.1    71.3    70.5    70.2
    70.3    70.1      70    70.7    71.7
    3526    3530    3701    3801  3943.4  4413.4  4614.3  4804.3 4829.34 4861.81
 4937.42  4970.3 4983.91 4986.14  4986.9 4987.13  4987.3 4987.39 5014.48 5014.59
 5020.76 5054.46 5075.99  5130.8 5156.03  5204.6  5345.6  5635.6  5805.6  6005.6
  6165.6  6585.6  6665.6  6735.6  6935.6  7175.6  7385.6  7405.6  7475.6  7875.6
  7995.6  8195.6  8455.6  8601.6    8604
    71.6    70.5    70.8    70.7    70.1    70.2    69.8   69.82   69.85   69.95
   70.48    70.7   70.69   70.69   70.69   70.69   70.69   70.69   70.67   70.67
   70.67   70.65   70.63    70.6    70.4   70.05    71.1    71.2    70.7    71.6
    71.6    70.2      70    70.6    70.6      70    71.1    71.3    70.5    70.2
    70.3    70.1      70    70.7    71.7
    71.5    70.4    70.7    70.6      70    70.1    69.7    69.4   69.69   69.64
   69.87   70.22   70.37   63.52   63.95   63.54   63.53   69.39   69.37   67.28
   70.12   70.23   69.91   69.69   69.57   69.94      71    71.1    70.6    71.5
    71.5    70.1    69.9    70.5    70.5    69.9      71    71.2    70.4    70.1
    70.2      70    69.9    70.6    71.6
Pier Skew, UpSta & Num, DnSta & Num=  ,4988.4, 2 ,4988.4, 2 , 0 , 0 , 0 ,,
       1       1
   62.56   70.49
       1       1
   62.46   70.39
Pier Skew, UpSta & Num, DnSta & Num=  ,4996.9, 2 ,4996.9, 2 , 0 , 0 , 0 ,,
       1       1
   62.53   70.48
       1       1
   62.43   70.38
Abutment Skew #Up #Dn= , 2 , 2
 4987.19 4988.67
   69.49   63.57
 4987.19 4988.67
   69.39   63.47
Abutment Skew #Up #Dn= , 2 , 2
 5011.78 5014.68
   66.09   69.47
 5011.78 5014.68
   65.99   69.37
BR Coef= 1 , 1 , 0 ,1.25, 0 ,,,.8,0,2,0,
WSPro=,,,, 1 ,,,, 0 ,,,, 0 ,,,,-1 ,-1 ,-1 , 0 , 0 , 0 , 0 , 0
BR U #Sta/Elev= 63
    3526    71.6    3530    70.5    3701    70.8    3801    70.7  3943.4    70.1
  4153.4    70.1  4413.4    70.2  4614.3    69.8  4802.6    69.5  4804.3    69.5
 4829.34   69.79  4850.1   69.76 4861.81   69.74  4885.9   69.84 4893.37   69.87
  4924.3   69.94 4937.42   69.97  4970.3   70.32 4983.91   70.47 4986.14   63.62
  4986.9   64.05 4987.13   63.64  4987.3   63.63 4987.39   63.63 4988.67   63.57
 4992.11   63.42 4996.32   63.52 5007.51   64.12 5011.78   66.09 5014.48   67.33
 5014.59   67.38 5020.76   70.22 5054.46   70.33 5075.99   70.01  5130.8   69.79
 5155.88   69.69 5156.03   69.67  5204.6   70.04  5253.6   70.41  5345.6    71.1
  5635.6    71.2  5805.6    70.7  6005.6    71.6  6131.2    71.6  6165.6    71.6
  6585.6    70.2    6601   70.16  6665.6      70  6735.6    70.6  6935.6    70.6
  7075.6    70.3  7175.6      70  7385.6    71.1  7405.6    71.3  7475.6    70.5
  7665.6    70.4  7875.6    70.2  7995.6    70.3  8195.6    70.1  8305.6    70.1
  8455.6      70  8601.6    70.7    8604    71.7
BR U #Mann= 5
    3526      .1 4983.91     .04 5020.76      .1  6131.2      .2    6601     .99
BR U Banks=4983.91,5020.76
BR D #Sta/Elev= 63
    3526    71.5    3530    70.4    3701    70.7    3801    70.6  3943.4      70
  4153.4      70  4413.4    70.1  4614.3    69.7  4802.6    69.4  4804.3    69.4
 4829.34   69.69  4850.1   69.66 4861.81   69.64  4885.9   69.74 4893.37   69.77
  4924.3   69.84 4937.42   69.87  4970.3   70.22 4983.91   70.37 4986.14   63.52
  4986.9   63.95 4987.13   63.54  4987.3   63.53 4987.39   63.53 4988.67   63.47
 4992.11   63.32 4996.32   63.42 5007.51   64.02 5011.78   65.99 5014.48   67.23
 5014.59   67.28 5020.76   70.12 5054.46   70.23 5075.99   69.91  5130.8   69.69
 5155.88   69.59 5156.03   69.57  5204.6   69.94  5253.6   70.31  5345.6      71
  5635.6    71.1  5805.6    70.6  6005.6    71.5  6131.2    71.5  6165.6    71.5
  6585.6    70.1    6601   70.06  6665.6    69.9  6735.6    70.5  6935.6    70.5
  7075.6    70.2  7175.6    69.9  7385.6      71  7405.6    71.2  7475.6    70.4
  7665.6    70.3  7875.6    70.1  7995.6    70.2  8195.6      70  8305.6      70
  8455.6    69.9  8601.6    70.6    8604    71.6
BR D #Mann= 5
    3526      .1 4983.91     .04 5020.76      .1  6131.2      .2    6601     .99
BR D Banks=4983.91,5020.76
BC Design=,, 0 ,, 0 ,,,,,,

Type RM Length L Ch R = 1 ,4904.5  ,121.4,121.4,121.4
BEGIN DESCRIPTION:
Downstream Section of Bridge/Culvert/Weir
END DESCRIPTION:
XS GIS Cut Line= 6
      3113991.71     13886033.03      3114907.91     13886095.91
      3115404.17     13886001.81      3115490.07     13885842.77
      3115603.72     13885742.94      3118925.35     13885798.76
#Sta/Elev= 30
    3526   71.47    3530   70.37    3701   70.67  3943.4   69.97  4413.4   70.07
  4804.3   69.37 4937.42   69.84 4983.91   70.34 4986.14   63.49  4986.9   63.92
 4987.13   63.51 4992.11   63.29 5007.51   63.99 5020.76   70.09 5156.03   69.54
  5345.6   70.97  5635.6   71.07  5805.6   70.57  6005.6   71.47  6131.2   71.47
    6601   70.03  6665.6   69.87  6735.6   70.47  6935.6   70.47  7175.6   69.87
  7405.6   71.17  7475.6   70.37  8455.6   69.87  8601.6   70.57    8604   71.57
#Mann= 5 , 1 , 0
    3526      .1       0 4983.91     .04       0 5020.76      .1       0
  6131.2      .2       0    6601     .99       0
#XS Ineff= 2 , 0
       0    4977    69.6    5025       0      70
Permanent Ineff=
       F       F
Bank Sta=4983.91,5020.76
XS Rating Curve= 0
Exp/Cntr=.5,.3

Type RM Length L Ch R = 1 ,4783.1  ,161.5,201.05,136.7
BEGIN DESCRIPTION:
Cross Section 4783.1-Interpolated
END DESCRIPTION:
XS GIS Cut Line= 6
      3114121.94     13886126.61      3114421.92     13886152.84
      3115319.79     13886147.12      3115605.73     13886015.59
      3115914.55     13885855.46      3118314.18     13885896.35
#Sta/Elev= 30
  3599.1    71.6  3940.2    69.7  4060.2    69.9  4100.2    70.4  4450.2    69.7
  4730.2    70.4  4798.1      71  4986.3   69.54  4995.6   64.01  4998.3   63.03
    5002   62.94  5003.8    63.3  5004.5   63.99  5015.2   69.03  5038.1    71.3
  5112.9    70.8  5222.9    69.8  5966.9   69.94  6244.1   70.19  6370.7    70.3
  6460.7    69.7  6502.1   69.91  6780.7    71.3  6870.7    70.9  7170.7    70.8
  7240.7    71.2  7260.7      69  7280.7    69.6  7390.7      71  7860.7    71.6
#Mann= 6 , 1 , 0
  3599.1      .1       0  4986.3     .04       0  5015.2      .1       0
  5966.9     .07       0  6244.1      .2       0  6502.1     .99       0
Bank Sta=4986.3,5015.2
XS Rating Curve= 0
Exp/Cntr=.5,.3

Type RM Length L Ch R = 1 ,4582.1  ,27.1,27.1,27.1
BEGIN DESCRIPTION:
Upstream Section of Bridge/Culvert/Weir
END DESCRIPTION:
XS GIS Cut Line= 6
      3114270.71     13886271.79       3115251.2     13886306.97
      3115515.47       13886286.      3115796.74     13886112.16
      3116154.85     13886001.31      3118868.39      13886090.4
#Sta/Elev= 30
  3630.7   71.51  3633.7   70.61  3665.7   69.81  4360.2   70.41  4610.2   69.61
  4901.1   69.73  4979.3   70.54  4986.3   69.28  4995.3   64.67  4995.6   63.75
  4998.3   62.77    5002   62.68  5003.8   63.04  5005.1    64.5  5015.1   68.77
  5015.8   69.83  5413.4   69.81  5583.4   70.81  5817.7   70.01  5867.7   70.91
  6025.4   71.51  6399.7   70.21  6827.7   69.71  7007.7   70.31  7097.7   71.91
  7327.7   69.81  7717.7   71.01  8057.7   69.71  8267.7   70.11  8297.7   71.61
#Mann= 5 , 1 , 0
  3630.7      .1       0  4986.3     .04       0  5015.1      .1       0
  6025.4      .2       0  6399.7     .99       0
#XS Ineff= 2 , 0
       0    4974    69.7    5025       0    69.2
Permanent Ineff=
       F       F
Bank Sta=4986.3,5015.1
XS Rating Curve= 0
Exp/Cntr=.5,.3