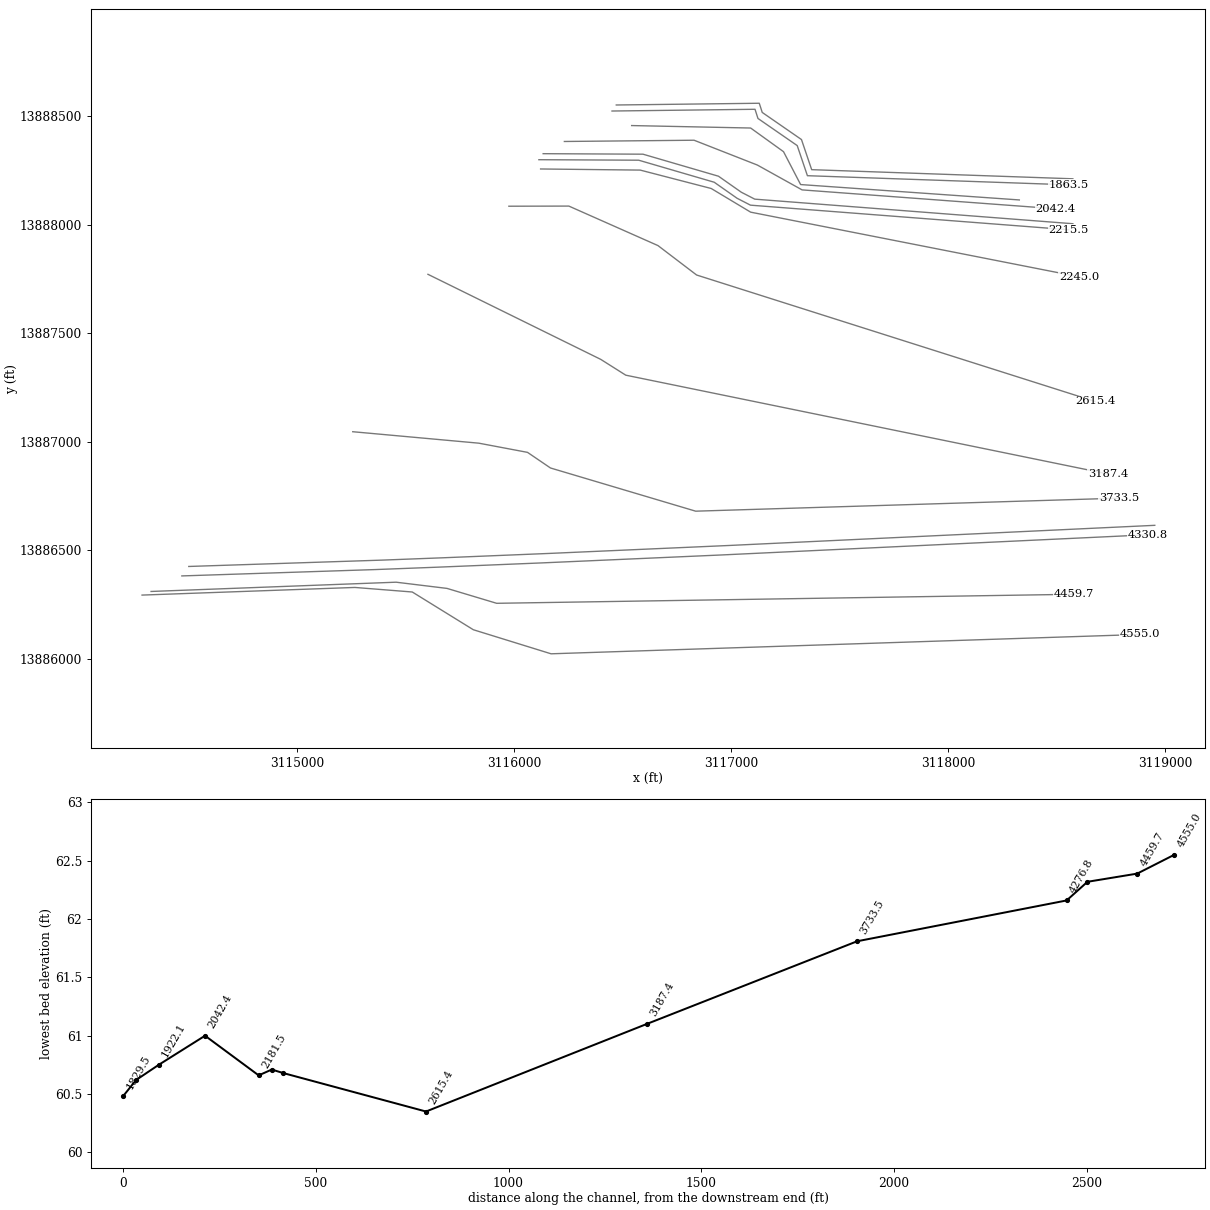
HEC-RAS study P118-23-00.PRJ: P118-23-00

--- P118-23-00.g01 (geometry) --- (continued)

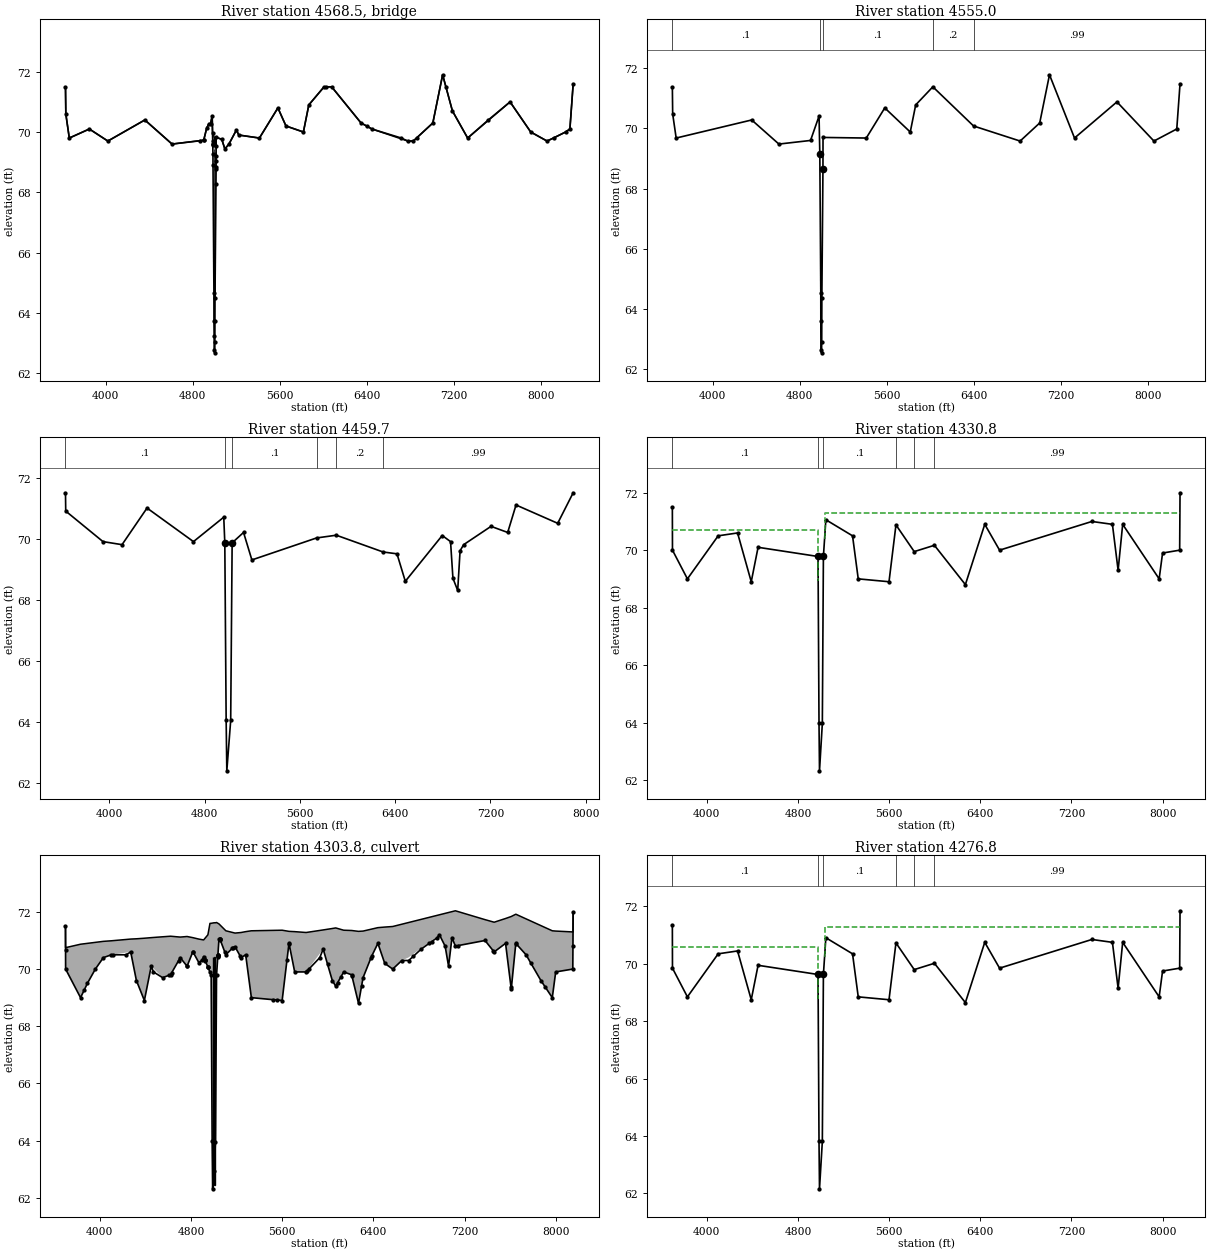
Type RM Length L Ch R = 3 ,4568.5  ,,,
BEGIN DESCRIPTION:
FOOTBRIDGE 2
Structure ID: P83-6B,,,,
END DESCRIPTION:
Bridge Culvert--1,0,-1,-1, 0
Deck Dist Width WeirC Skew NumUp NumDn MinLoCord MaxHiCord MaxSubmerge Is_Ogee
10,7.1,2.6,0, 44, 44, , , .95, 0, 1,1,,
  3630.7  3633.7  3665.7  3850.2  4020.2  4360.2  4610.2  4901.1  4928.4  4949.2
    4964  4979.3  4982.4  4984.6 5015.29  5015.4  5015.6  5015.8  5067.2  5095.7
  5131.9  5202.3  5223.4  5413.4  5583.4  5657.7  5817.7  5867.7  6007.7  6077.7
  6347.7  6447.7  6777.7  6827.7  7007.7  7097.7  7187.7  7327.7  7717.7  7907.7
  8057.7  8227.7  8267.7  8297.7
    71.5    70.6    69.8    70.1    69.7    70.4    69.6   69.73   70.13   70.28
   70.28   70.54   69.98   69.98   69.61   69.61   69.61   69.82   69.76   69.44
   69.59   70.07    69.9    69.8    70.8    70.2      70    70.9    71.5    71.5
    70.3    70.1    69.7    69.7    70.3    71.9    70.7    69.8      71      70
    69.7      70    70.1    71.6
    71.5    70.6    69.8    70.1    69.7    70.4    69.6   69.72   70.12   70.27
   70.27   70.53   69.97   69.58   69.21   69.21   69.52   69.82   69.76   69.44
   69.59   70.07    69.9    69.8    70.8    70.2      70    70.9    71.5    71.5
    70.3    70.1    69.7    69.7    70.3    71.9    70.7    69.8      71      70
    69.7      70    70.1    71.6
  3630.7  3633.7  3665.7  3850.2  4020.2  4360.2  4610.2  4901.1  4928.4  4949.2
    4964  4979.3  4982.4  4984.6 5015.29  5015.4  5015.6  5015.8  5067.2  5095.7
  5131.9  5202.3  5223.4  5413.4  5583.4  5657.7  5817.7  5867.7  6007.7  6077.7
  6347.7  6447.7  6777.7  6827.7  7007.7  7097.7  7187.7  7327.7  7717.7  7907.7
  8057.7  8227.7  8267.7  8297.7
    71.5    70.6    69.8    70.1    69.7    70.4    69.6   69.73   70.13   70.28
   70.28   70.54   69.98   69.98   69.61   69.61   69.61   69.82   69.76   69.44
   69.59   70.07    69.9    69.8    70.8    70.2      70    70.9    71.5    71.5
    70.3    70.1    69.7    69.7    70.3    71.9    70.7    69.8      71      70
    69.7      70    70.1    71.6
    71.4    70.5    69.7      70    69.6    70.3    69.5   69.62   70.02   70.17
   70.17   70.43   69.87   69.48   69.11   69.11   69.42   69.72   69.66   69.34
   69.49   69.97    69.8    69.7    70.7    70.1    69.9    70.8    71.4    71.4
    70.2      70    69.6    69.6    70.2    71.8    70.6    69.7    70.9    69.9
    69.6    69.9      70    71.5
Pier Skew, UpSta & Num, DnSta & Num=  ,4995.3, 2 ,4995.3, 2 , 0 , 0 , 0 ,,
      .5      .5
   62.89   70.45
      .5      .5
   62.79   70.35
Pier Skew, UpSta & Num, DnSta & Num=  ,5005.1, 2 ,5005.1, 2 , 0 , 0 , 0 ,,
      .5      .5
   63.17   70.34
      .5      .5
   63.07   70.24
BR Coef= 1 , 1 , 0 ,1.25, 0 ,,,.8,0,2,0,
WSPro=,,,, 1 ,,,, 0 ,,,, 0 ,,,,-1 ,-1 ,-1 , 0 , 0 , 0 , 0 , 0
BR U #Sta/Elev= 69
  3630.7    71.5  3633.7    70.6  3665.7    69.8  3850.2    70.1  4020.2    69.7
  4360.2    70.4  4610.2    69.6  4868.5   69.71    4901   69.72  4901.1   69.72
  4928.4   70.12  4949.2   70.27    4964   70.27  4979.3   70.53  4982.4   69.97
  4983.9    69.7 4984.41   69.61  4984.5   69.59  4984.6   69.58  4986.3   69.27
  4986.8   68.92  4995.3   64.66  4995.6   63.74  4997.1   63.22  4998.3   62.76
    5002   62.67  5003.8   63.03  5004.5   63.72  5005.1   64.49  5014.1   68.27
  5015.1   68.76 5015.15   68.84 5015.29   69.05  5015.4   69.21  5015.6   69.52
  5015.8   69.82  5067.2   69.76  5095.7   69.44  5131.9   69.59  5202.3   70.07
  5223.4    69.9  5413.4    69.8  5583.4    70.8  5657.7    70.2  5817.7      70
  5867.7    70.9  6007.7    71.5  6025.4    71.5  6077.7    71.5  6347.7    70.3
  6399.7    70.2  6447.7    70.1  6717.7    69.8  6777.7    69.7  6827.7    69.7
  6857.7    69.8  7007.7    70.3  7097.7    71.9  7127.7    71.5  7187.7    70.7
  7327.7    69.8  7517.7    70.4  7717.7      71  7907.7      70  8057.7    69.7
  8117.7    69.8  8227.7      70  8267.7    70.1  8297.7    71.6
BR U #Mann= 5
  3630.7      .1  4986.3     .04  5015.1      .1  6025.4      .2  6399.7     .99
BR U Banks=4986.3,5015.1
BR D #Sta/Elev= 69
  3630.7    71.4  3633.7    70.5  3665.7    69.7  3850.2      70  4020.2    69.6
  4360.2    70.3  4610.2    69.5  4868.5   69.61    4901   69.62  4901.1   69.62
  4928.4   70.02  4949.2   70.17    4964   70.17  4979.3   70.43  4982.4   69.87
  4983.9    69.6 4984.41   69.51  4984.5   69.49  4984.6   69.48  4986.3   69.17
  4986.8   68.82  4995.3   64.56  4995.6   63.64  4997.1   63.12  4998.3   62.66
    5002   62.57  5003.8   62.93  5004.5   63.62  5005.1   64.39  5014.1   68.17
  5015.1   68.66 5015.15   68.74 5015.29   68.95  5015.4   69.11  5015.6   69.42
  5015.8   69.72  5067.2   69.66  5095.7   69.34  5131.9   69.49  5202.3   69.97
  5223.4    69.8  5413.4    69.7  5583.4    70.7  5657.7    70.1  5817.7    69.9
  5867.7    70.8  6007.7    71.4  6025.4    71.4  6077.7    71.4  6347.7    70.2
  6399.7    70.1  6447.7      70  6717.7    69.7  6777.7    69.6  6827.7    69.6
  6857.7    69.7  7007.7    70.2  7097.7    71.8  7127.7    71.4  7187.7    70.6
  7327.7    69.7  7517.7    70.3  7717.7    70.9  7907.7    69.9  8057.7    69.6
  8117.7    69.7  8227.7    69.9  8267.7      70  8297.7    71.5
BR D #Mann= 5
  3630.7      .1  4986.3     .04  5015.1      .1  6025.4      .2  6399.7     .99
BR D Banks=4986.3,5015.1
BC Design=,, 0 ,, 0 ,,,,,,

Type RM Length L Ch R = 1 ,4555.0  ,95.25,95.25,95.25
BEGIN DESCRIPTION:
Downstream Section of Bridge/Culvert/Weir
END DESCRIPTION:
XS GIS Cut Line= 6
      3114286.73     13886293.65      3115267.22     13886328.83
      3115531.49     13886307.86      3115812.76     13886134.02
      3116170.87     13886023.17       3118884.4     13886112.26
#Sta/Elev= 30
  3630.7   71.38  3633.7   70.48  3665.7   69.68  4360.2   70.28  4610.2   69.48
  4901.1    69.6  4979.3   70.41  4986.3   69.15  4995.3   64.54  4995.6   63.62
  4998.3   62.64    5002   62.55  5003.8   62.91  5005.1   64.37  5015.1   68.64
  5015.8    69.7  5413.4   69.68  5583.4   70.68  5817.7   69.88  5867.7   70.78
  6025.4   71.38  6399.7   70.08  6827.7   69.58  7007.7   70.18  7097.7   71.78
  7327.7   69.68  7717.7   70.88  8057.7   69.58  8267.7   69.98  8297.7   71.48
#Mann= 5 , 1 , 0
  3630.7      .1       0  4986.3     .04       0  5015.1      .1       0
  6025.4      .2       0  6399.7     .99       0
#XS Ineff= 2 , 0
       0    4974    69.7    5025       0    69.2
Permanent Ineff=
       F       F
Bank Sta=4986.3,5015.1
XS Rating Curve= 0
Exp/Cntr=.5,.3

Type RM Length L Ch R = 1 ,4459.7  ,75.2,128.9,234.7
BEGIN DESCRIPTION:
Cross Section 4459.7-Interpolated
END DESCRIPTION:
XS GIS Cut Line= 5
      3114328.31     13886310.33      3115457.04       13886353.
      3115691.51     13886324.41      3115920.27     13886255.78
      3118579.97     13886297.37
#Sta/Elev= 30
  3631.3    71.5  3633.3    70.9  3946.3    69.9  4106.3    69.8  4316.3      71
  4706.3    69.9  4960.8    70.7  4969.6   69.86  4980.9   64.05  4986.5   62.39
    5019   64.04  5031.2   69.86    5127    70.2    5197    69.3  5740.4   70.02
  5906.1   70.11  6299.3   69.56  6415.9    69.5  6485.9    68.6  6795.9    70.1
  6865.9    69.9  6885.9    68.7  6925.9    68.3  6945.9    69.6  6975.9    69.8
  7205.9    70.4  7345.9    70.2  7415.9    71.1  7765.9    70.5  7895.9    71.5
#Mann= 6 , 1 , 0
  3631.3      .1       0  4969.6     .04       0  5031.2      .1       0
  5740.4     .07       0  5906.1      .2       0  6299.3     .99       0
Bank Sta=4969.6,5031.2
XS Rating Curve= 0
Exp/Cntr=.5,.3

Type RM Length L Ch R = 1 ,4330.8  ,54,54,54
BEGIN DESCRIPTION:
Upstream Section of Bridge/Culvert/Weir
END DESCRIPTION:
XS GIS Cut Line= 6
      3114470.02     13886381.92      3115361.09     13886411.18
      3115644.72     13886422.06      3116132.23     13886442.05
      3116955.57     13886478.45      3118919.92     13886571.44
#Sta/Elev= 30
  3698.7   71.51  3699.8   70.01  3830.8   69.01  4100.8   70.51  4270.8   70.61
  4390.8   68.91  4450.8   70.11 4976.71   69.79 4985.37   63.98 4989.66   62.32
 5014.55   63.97  5023.9   69.79 5045.42   71.07  5279.5   70.51  5329.5   69.01
  5599.5   68.91  5660.5   70.89  5820.7   69.96  5997.7   70.18  6269.5   68.81
  6439.5   70.91  6569.5   70.01  7379.5   71.01  7559.5   70.91  7609.5   69.31
  7649.5   70.91  7969.5   69.01  7999.5   69.91  8149.5   70.01  8152.7   72.01
#Mann= 6 , 1 , 0
  3698.7      .1       0 4976.71     .04       0  5023.9      .1       0
  5660.5     .07       0  5820.7      .2       0  5997.7     .99       0
#XS Ineff= 2 , 0
       0    4978    70.7    5034       0    71.3
Permanent Ineff=
       F       F
Bank Sta=4976.71,5023.9
XS Rating Curve= 0
Exp/Cntr=.5,.3

Type RM Length L Ch R = 2 ,4303.8  ,,,
BEGIN DESCRIPTION:
EAST MITCHELL ROAD, SKEW ANGLE OF 40 DEGREES
Structure ID: P83-5
END DESCRIPTION:
Bridge Culvert--1,0,-1,-1, 0
Deck Dist Width WeirC Skew NumUp NumDn MinLoCord MaxHiCord MaxSubmerge Is_Ogee
10,34,3,0, 60, 60, , , .95, 0, 1,1,,
  3698.7  3699.3  3699.8  3830.8  4030.8  4100.8  4270.8  4320.8  4390.8  4450.8
  4550.8  4620.8  4705.4  4765.4  4815.7 4868.09 4910.68 4948.11  4966.2 4976.71
 4985.37 4989.66 5001.61 5014.55  5023.9 5045.42 5105.63 5186.14  5239.5  5279.5
  5329.5  5599.5  5659.5  5709.5  5809.5  5959.5  6039.5  6069.5  6139.5  6209.5
  6269.5  6309.5  6439.5  6499.5  6569.5  6979.5  7029.5  7059.5  7089.5  7119.5
  7379.5  7459.5  7559.5  7609.5  7649.5  7969.5  7999.5  8149.5  8150.8  8152.7
    71.5   70.75   70.75   70.87   70.97   70.99   71.05   71.06   71.08    71.1
   71.13   71.15   71.12   71.14    71.1   71.05   71.02    71.2    71.6    71.6
   71.61   71.61   71.62   71.62   71.63   71.58   71.34   71.26   71.28   71.31
   71.34   71.36   71.32   71.31   71.28   71.37   71.42   71.44   71.36   71.35
   71.32   71.33   71.45   71.47   71.49    71.9   71.95   71.98   72.01   72.04
   71.73   71.64   71.77   71.84   71.92   71.34   71.33    71.3    71.3      72
    71.5   70.68      70      69    70.4    70.5    70.6    69.6    68.9    70.1
    69.7    69.8    70.4    70.1   70.61   70.23   70.44   70.07   69.89   69.78
   63.97   62.31   62.93   63.96   69.78   71.06    70.5   70.78    70.4    70.5
      69    68.9    70.9    69.9    69.9    70.7    69.6    69.4    69.9    69.8
    68.8    69.7    70.9    70.2      70    71.2    70.8    70.1    71.1    70.8
      71    70.6    70.9    69.3    70.9      69    69.9      70   70.81      72
  3698.7  3699.3  3699.8  3830.8  4030.8  4100.8  4270.8  4320.8  4390.8  4450.8
  4550.8  4620.8  4705.4  4765.4  4815.7 4868.09 4910.68 4948.11  4966.2 4976.71
 4985.37 4989.66 5001.61 5014.55  5023.9 5045.42 5105.63 5186.14  5239.5  5279.5
  5329.5  5599.5  5659.5  5709.5  5809.5  5959.5  6039.5  6069.5  6139.5  6209.5
  6269.5  6309.5  6439.5  6499.5  6569.5  6979.5  7029.5  7059.5  7089.5  7119.5
  7379.5  7459.5  7559.5  7609.5  7649.5  7969.5  7999.5  8149.5  8150.8  8152.7
    71.5   70.75   70.75   70.87   70.97   70.99   71.05   71.06   71.08    71.1
   71.13   71.15   71.12   71.14    71.1   71.05   71.02    71.2    71.6    71.6
   71.61   71.61   71.62   71.62   71.63   71.58   71.34   71.26   71.28   71.31
   71.34   71.36   71.32   71.31   71.28   71.37   71.42   71.44   71.36   71.35
   71.32   71.33   71.45   71.47   71.49    71.9   71.95   71.98   72.01   72.04
   71.73   71.64   71.77   71.84   71.92   71.34   71.33    71.3    71.3      72
   71.36   70.54   69.86   68.86   70.26   70.36   70.46   69.46   68.76   69.96
   69.56   69.66   70.26   69.96   70.47   70.09    70.3   69.93   69.75   69.64
   63.83   62.17   62.79   63.82   69.64   70.92   70.36   70.64   70.26   70.36
   68.86   68.76   70.76   69.76   69.76   70.56   69.46   69.26   69.76   69.66
   68.66   69.56   70.76   70.06   69.86   71.06   70.66   69.96   70.96   70.66
   70.86   70.46   70.76   69.16   70.76   68.86   69.76   69.86   70.67   71.86
BR Coef= 1 , 0 , 0 ,1.25, 0 ,,,.8,-1,2,0,
WSPro=,,,, 1 ,,,, 0 ,,,, 0 ,,,,-1 ,-1 ,-1 , 0 , 0 , 0 , 0 , 0
Culvert=2,8,8.4,34,.015,.5,1,8,1,62.42,4992.8,62.12,4992.8,Culvert #1  , 0 ,10
Culvert Bottom n=.015
Culvert=2,8,8.4,34,.015,.5,1,8,1,62.44,5008.7,62.14,5008.7,Culvert #2  , 0 ,10
Culvert Bottom n=.015
BR U #Sta/Elev= 121
  3698.7    71.5  3699.3   70.68  3699.8      70  3830.8      69  3864.8   69.28
  3890.8    69.5  3960.8      70  4030.8    70.4  4100.8    70.5  4114.8    70.5
  4230.8    70.5  4270.8    70.6  4320.8    69.6  4390.8    68.9  4450.8    70.1
  4470.8    69.9  4550.8    69.7  4605.2   69.78  4620.8    69.8  4630.2   69.87
  4690.2   70.29  4705.4    70.4  4765.2    70.1  4765.4    70.1 4815.62    70.6
  4815.7   70.61 4868.09   70.23 4897.36   70.31 4910.68   70.44 4922.19   70.32
  4922.3   70.32 4922.41   70.32  4925.2   70.29 4947.89   70.07    4948   70.07
 4948.11   70.07  4966.2   69.89 4976.71   69.78 4985.37   63.97 4989.66   62.31
 5001.61   62.93 5014.55   63.96  5023.9   69.78 5034.99   70.44  5035.1   70.45
 5035.21   70.45 5035.59   70.48  5035.7   70.48 5035.81   70.49 5045.42   71.06
 5050.09   71.04  5050.2   71.04 5050.31   71.04 5058.14      71    5096    70.6
 5105.63    70.5  5162.6   70.73 5167.29   70.75 5186.14   70.78  5230.7   70.46
  5239.5    70.4  5279.5    70.5  5329.5      69    5517   68.93    5557   68.92
  5599.5    68.9    5642   70.32  5659.5    70.9  5660.5   70.88  5709.5    69.9
  5809.5    69.9  5820.7   69.95    5832   69.99  5929.5    70.4  5959.5    70.7
  5997.7   70.17  6039.5    69.6  6069.5    69.4    6087   69.53    6117   69.74
  6139.5    69.9  6209.5    69.8  6211.1   69.77  6269.5    68.8  6296.1    69.4
  6309.5    69.7  6379.5    70.4  6386.1   70.46  6439.5    70.9  6499.5    70.2
  6569.5      70  6649.5    70.3  6709.5    70.3  6751.1   70.45  6819.5    70.7
  6889.5    70.9  6911.1   70.96  6959.5    71.1  6979.5    71.2  7029.5    70.8
  7059.5    70.1  7089.5    71.1  7119.5    70.8  7141.1   70.82  7379.5      71
  7451.1   70.64  7459.5    70.6  7559.5    70.9  7609.5    69.3  7611.1   69.36
  7649.5    70.9  7651.1   70.89  7739.5    70.5  7781.1   70.21  7869.5    69.6
  7906.1   69.38  7969.5      69  7999.5    69.9  8149.5      70  8150.8   70.81
  8152.7      72
BR U #Mann= 6
  3698.7      .1 4976.71     .04  5023.9      .1  5660.5     .07  5820.7      .2
  5997.7     .99
BR U Banks=4976.71,5023.9
BR D #Sta/Elev= 121
  3698.7   71.36  3699.3   70.54  3699.8   69.86  3830.8   68.86  3864.8   69.14
  3890.8   69.36  3960.8   69.86  4030.8   70.26  4100.8   70.36  4114.8   70.36
  4230.8   70.36  4270.8   70.46  4320.8   69.46  4390.8   68.76  4450.8   69.96
  4470.8   69.76  4550.8   69.56  4605.2   69.64  4620.8   69.66  4630.2   69.73
  4690.2   70.15  4705.4   70.26  4765.2   69.96  4765.4   69.96 4815.62   70.46
  4815.7   70.47 4868.09   70.09 4897.36   70.17 4910.68    70.3 4922.19   70.18
  4922.3   70.18 4922.41   70.18  4925.2   70.15 4947.89   69.93    4948   69.93
 4948.11   69.93  4966.2   69.75 4976.71   69.64 4985.37   63.83 4989.66   62.17
 5001.61   62.79 5014.55   63.82  5023.9   69.64 5034.99    70.3  5035.1   70.31
 5035.21   70.31 5035.59   70.34  5035.7   70.34 5035.81   70.35 5045.42   70.92
 5050.09    70.9  5050.2    70.9 5050.31    70.9 5058.14   70.86    5096   70.46
 5105.63   70.36  5162.6   70.59 5167.29   70.61 5186.14   70.64  5230.7   70.32
  5239.5   70.26  5279.5   70.36  5329.5   68.86    5517   68.79    5557   68.78
  5599.5   68.76    5642   70.18  5659.5   70.76  5660.5   70.74  5709.5   69.76
  5809.5   69.76  5820.7   69.81    5832   69.85  5929.5   70.26  5959.5   70.56
  5997.7   70.03  6039.5   69.46  6069.5   69.26    6087   69.39    6117    69.6
  6139.5   69.76  6209.5   69.66  6211.1   69.63  6269.5   68.66  6296.1   69.26
  6309.5   69.56  6379.5   70.26  6386.1   70.32  6439.5   70.76  6499.5   70.06
  6569.5   69.86  6649.5   70.16  6709.5   70.16  6751.1   70.31  6819.5   70.56
  6889.5   70.76  6911.1   70.82  6959.5   70.96  6979.5   71.06  7029.5   70.66
  7059.5   69.96  7089.5   70.96  7119.5   70.66  7141.1   70.68  7379.5   70.86
  7451.1    70.5  7459.5   70.46  7559.5   70.76  7609.5   69.16  7611.1   69.22
  7649.5   70.76  7651.1   70.75  7739.5   70.36  7781.1   70.07  7869.5   69.46
  7906.1   69.24  7969.5   68.86  7999.5   69.76  8149.5   69.86  8150.8   70.67
  8152.7   71.86
BR D #Mann= 6
  3698.7      .1 4976.71     .04  5023.9      .1  5660.5     .07  5820.7      .2
  5997.7     .99
BR D Banks=4976.71,5023.9
BC Design=,, 0 ,, 0 ,,,,,,

Type RM Length L Ch R = 1 ,4276.8  ,543.3,543.3,543.3
BEGIN DESCRIPTION:
Downstream Section of Bridge/Culvert/Weir
END DESCRIPTION:
XS GIS Cut Line= 6
      3114501.94     13886425.47      3115393.01     13886454.74
      3115676.64     13886465.62      3116164.15     13886485.61
      3116987.49     13886522.01      3118951.84       13886615.
#Sta/Elev= 30
  3698.7   71.35  3699.8   69.85  3830.8   68.85  4100.8   70.35  4270.8   70.45
  4390.8   68.75  4450.8   69.95 4976.71   69.63 4985.37   63.82 4989.66   62.16
 5014.55   63.81  5023.9   69.63 5045.42   70.91  5279.5   70.35  5329.5   68.85
  5599.5   68.75  5660.5   70.73  5820.7    69.8  5997.7   70.02  6269.5   68.65
  6439.5   70.75  6569.5   69.85  7379.5   70.85  7559.5   70.75  7609.5   69.15
  7649.5   70.75  7969.5   68.85  7999.5   69.75  8149.5   69.85  8152.7   71.85
#Mann= 6 , 1 , 0
  3698.7      .1       0 4976.71     .04       0  5023.9      .1       0
  5660.5     .07       0  5820.7      .2       0  5997.7     .99       0
#XS Ineff= 2 , 0
       0    4978    70.6    5034       0    71.3
Permanent Ineff=
       F       F
Bank Sta=4976.71,5023.9
XS Rating Curve= 0
Exp/Cntr=.5,.3

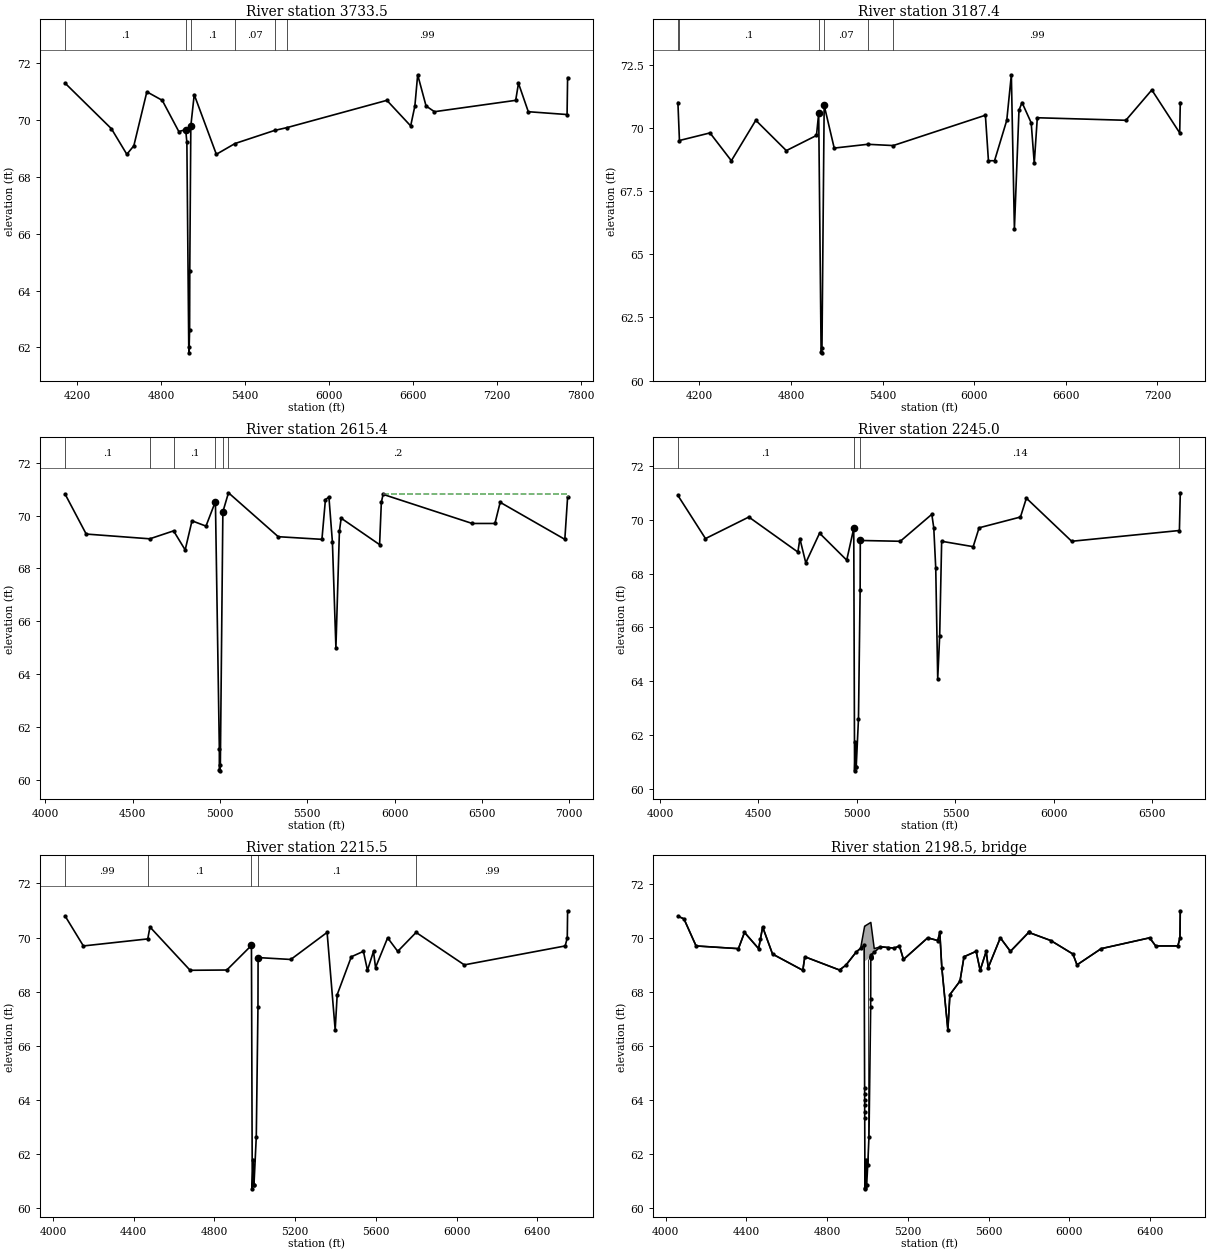
Type RM Length L Ch R = 1 ,3733.5  ,664.6,546.1,498.3
BEGIN DESCRIPTION:
Cross Section 3733.5
END DESCRIPTION:
XS GIS Cut Line= 6
       3115257.3      13887046.2      3115837.97     13886993.41
      3116062.33     13886951.08      3116168.16     13886879.11
        3116837.     13886680.15       3118786.8     13886740.18
#Sta/Elev= 30
  4115.4    71.3  4445.4    69.7  4555.4    68.8  4605.4    69.1  4698.4      71
  4808.4    70.7  4926.7    69.6  4975.6   69.67  4984.2   69.22  4997.6   62.03
  4999.5   61.81  5003.7   62.63  5004.9   64.69  5012.4    69.8  5036.7    70.9
  5194.7    68.8  5328.2   69.18  5610.3   69.64  5699.3   69.74  6412.5    70.7
  6582.5    69.8  6612.5    70.5  6632.5    71.6  6692.5    70.5  6752.5    70.3
  7332.5    70.7  7352.5    71.3  7422.5    70.3  7699.5    70.2  7703.3    71.5
#Mann= 6 , 1 , 0
  4115.4      .1       0  4975.6     .04       0  5012.4      .1       0
  5328.2     .07       0  5610.3      .1       0  5699.3     .99       0
Bank Sta=4975.6,5012.4
XS Rating Curve= 0
Exp/Cntr=.3,.1

Type RM Length L Ch R = 1 ,3187.4  ,578.7,572,459.1
BEGIN DESCRIPTION:
Cross Section 3187.4-Interpolated
END DESCRIPTION:
XS GIS Cut Line= 4
       3115603.7     13887771.29      3116399.89     13887379.32
      3116514.96     13887306.65      3118735.28     13886851.66
#Sta/Elev= 30
  4059.3      71  4069.3    69.5  4269.3    69.8  4409.3    68.7  4569.3    70.3
  4769.3    69.1  4966.8    69.7  4981.2   70.58    4997   61.15  4999.9    61.1
  5002.7   61.31  5017.1   70.89  5082.9    69.2  5302.1   69.35  5469.3    69.3
  6072.9    70.5  6092.9    68.7  6132.9    68.7  6212.9    70.3  6242.9    72.1
  6262.9      66  6292.9    70.7  6312.9      71  6372.9    70.2  6392.9    68.6
  6412.9    70.4  6992.9    70.3  7162.9    71.5  7345.4    69.8  7349.3      71
#Mann= 6 , 1 , 0
  4059.3      .2       0  4069.3      .1       0  4981.2     .04       0
  5017.1     .07       0  5302.1      .1       0  5469.3     .99       0
Bank Sta=4981.2,5017.1
XS Rating Curve= 0
Exp/Cntr=.3,.1

Type RM Length L Ch R = 1 ,2615.4  ,247.4,370.4,411.2
BEGIN DESCRIPTION:
Cross Section 2615.4
END DESCRIPTION:
XS GIS Cut Line= 5
      3115976.49     13888084.95      3116252.82     13888085.57
      3116663.44     13887903.54      3116841.23     13887768.08
      3118676.89     13887185.53
#Sta/Elev= 30
    4115    70.8    4235    69.3  4598.9   69.12  4735.1   69.42  4801.4    68.7
  4840.5    69.8  4920.5    69.6  4974.5   70.53  4996.9   61.19    4997    60.4
  4999.9   60.35  5002.7   60.56  5017.1   70.14  5049.2   70.86    5334    69.2
    5584    69.1    5604    70.6    5624    70.7    5644      69    5664      65
    5684    69.4    5694    69.9    5914    68.9    5924    70.5    5934    70.8
    6444    69.7    6574    69.7    6604    70.5    6974    69.1  6989.9    70.7
#Mann= 6 , 1 , 0
    4115      .1       0  4598.9     .07       0  4735.1      .1       0
  4974.5     .04       0  5017.1     .07       0  5049.2      .2       0
#XS Ineff= 2 , 0
       0                    5934       0    70.8
Permanent Ineff=
       F       F
Bank Sta=4974.5,5017.1
XS Rating Curve= 0
Exp/Cntr=.3,.1

Type RM Length L Ch R = 1 ,2245.0  ,27.2,29.5,95.9
BEGIN DESCRIPTION:
Cross Section 2245.0-Interpolated
END DESCRIPTION:
XS GIS Cut Line= 5
      3116122.64     13888256.51      3116581.57     13888251.36
      3116908.58     13888166.58      3117090.26     13888057.57
       3118602.6     13887759.97
#Sta/Elev= 30
  4091.1    70.9  4231.1    69.3  4451.1    70.1  4700.1    68.8  4710.1    69.3
  4740.1    68.4  4810.1    69.5  4947.9    68.5  4983.6   69.68  4987.8   60.68
  4992.3   61.76    4994   60.81  4996.2   60.84  5007.6   62.61    5016   67.39
  5016.8   69.23  5219.8    69.2  5379.8    70.2  5389.8    69.7  5399.8    68.2
  5409.8    64.1  5419.8    65.7  5429.8    69.2  5589.8      69  5619.8    69.7
  5829.8    70.1  5859.8    70.8  6089.8    69.2  6636.6    69.6  6641.1      71
#Mann= 4 , 1 , 0
  4091.1      .1       0  4983.6     .04       0  5016.8     .14       0
  6636.6      .2       0
#XS Ineff= 2 , 0
       0                  5859.8       0    70.8
Permanent Ineff=
       F       F
Bank Sta=4983.6,5016.8
XS Rating Curve= 0
Exp/Cntr=.5,.3

Type RM Length L Ch R = 1 ,2215.5  ,34,34,34
BEGIN DESCRIPTION:
Upstream Section of Bridge/Culvert/Weir
END DESCRIPTION:
XS GIS Cut Line= 6
      3116114.74     13888299.25      3116574.58      13888296.9
      3116922.34     13888195.44      3117027.61     13888121.62
      3117089.47     13888089.81      3118554.84     13887976.59
#Sta/Elev= 30
  4060.6   70.79  4150.6   69.69  4469.7   69.95  4480.6   70.39  4679.6   68.79
  4861.5    68.8  4983.6   69.71  4987.7   60.71  4992.3   61.79    4994   60.84
  4996.2   60.87  5007.6   62.64  5015.9   67.42  5016.5   69.26  5178.6   69.19
  5358.6   70.19  5398.6   66.59  5408.6   67.89  5478.6   69.29  5538.6   69.49
  5558.6   68.79  5588.6   69.49  5598.6   68.89  5658.6   69.99  5708.6   69.49
  5799.7   70.19  6038.6   68.99  6538.6   69.69  6548.9   69.99  6550.6   70.99
#Mann= 5 , 1 , 0
  4060.6     .99       0  4469.7      .1       0  4983.6     .04       0
  5016.5      .1       0  5799.7     .99       0
#XS Ineff= 2 , 0
       0    4976    68.8    5027       0    67.9
Permanent Ineff=
       F       F
Bank Sta=4983.6,5016.5
XS Rating Curve= 0
Exp/Cntr=.5,.3

Type RM Length L Ch R = 3 ,2198.5  ,,,
BEGIN DESCRIPTION:
FOOTBRIDGE 1
Structure ID: P83-4,,,,
END DESCRIPTION:
Bridge Culvert--1,0,-1,-1, 0
Deck Dist Width WeirC Skew NumUp NumDn MinLoCord MaxHiCord MaxSubmerge Is_Ogee
10,14,2.6,0, 48, 48, , , .95, 0, 1,1,,
  4060.6  4090.6  4150.6  4360.6  4390.6  4460.6  4480.6  4529.6  4679.6  4689.6
  4861.5  4893.4  4943.7  4966.3  4983.6 4986.11  4986.2 5016.78    5018  5033.7
  5064.6  5133.1  5158.6  5178.6  5298.6  5348.6  5358.6  5368.6  5398.6  5408.6
  5458.6  5478.6  5538.6  5558.6  5588.6  5598.6  5658.6  5708.6  5799.7  5908.6
  6018.6  6038.6  6158.6  6398.6  6428.6  6538.6  6548.9  6550.6
    70.8    70.7    69.7    69.6    70.2    69.6    70.4    69.4    68.8    69.3
   68.81   68.99   69.47   69.62   70.33   70.43   70.43   70.57    70.5    69.6
   69.67   69.62    69.7    69.2      70    69.9    70.2    68.9    66.6    67.9
    68.4    69.3    69.5    68.8    69.5    68.9      70    69.5    70.2    69.9
    69.4      69    69.6      70    69.7    69.7      70      71
    70.8    70.7    69.7    69.6    70.2    69.6    70.4    69.4    68.8    69.3
   68.81   68.99   69.47   69.61   69.72   64.21   69.13   69.29   69.37   69.47
   69.67   69.62    69.7    69.2      70    69.9    70.2    68.9    66.6    67.9
    68.4    69.3    69.5    68.8    69.5    68.9      70    69.5    70.2    69.9
    69.4      69    69.6      70    69.7    69.7      70      71
  4060.6  4090.6  4150.6  4360.6  4390.6  4460.6  4480.6  4529.6  4679.6  4689.6
  4861.5  4893.4  4943.7  4966.3  4983.6 4986.11  4986.2 5016.78    5018  5033.7
  5064.6  5133.1  5158.6  5178.6  5298.6  5348.6  5358.6  5368.6  5398.6  5408.6
  5458.6  5478.6  5538.6  5558.6  5588.6  5598.6  5658.6  5708.6  5799.7  5908.6
  6018.6  6038.6  6158.6  6398.6  6428.6  6538.6  6548.9  6550.6
    70.8    70.7    69.7    69.6    70.2    69.6    70.4    69.4    68.8    69.3
   68.81   68.99   69.47   69.62   70.33   70.43   70.43   70.57    70.5    69.6
   69.67   69.62    69.7    69.2      70    69.9    70.2    68.9    66.6    67.9
    68.4    69.3    69.5    68.8    69.5    68.9      70    69.5    70.2    69.9
    69.4      69    69.6      70    69.7    69.7      70      71
   70.72   70.62   69.62   69.52   70.12   69.52   70.32   69.32   68.72   69.22
   68.73   68.91   69.39   69.53   69.64   64.13   69.05   69.21   69.29   69.39
   69.59   69.54   69.62   69.12   69.92   69.82   70.12   68.82   66.52   67.82
   68.32   69.22   69.42   68.72   69.42   68.82   69.92   69.42   70.12   69.82
   69.32   68.92   69.52   69.92   69.62   69.62   69.92   70.92
Pier Skew, UpSta & Num, DnSta & Num=  ,5001.4, 2 ,5001.4, 2 , 0 , 0 , 0 ,,
       1       1
   60.52    70.2
       1       1
   60.44   70.12
Abutment Skew #Up #Dn= , 2 , 2
    4986  4987.8
   69.13   60.74
    4986  4987.8
   69.05   60.66
Abutment Skew #Up #Dn= , 2 , 2
    5016 5017.09
   67.74    69.3
    5016 5017.09
   67.66   69.22
BR Coef= 1 , 1 , 0 ,1.25, 0 ,,,.8,0,2,0,
WSPro=,,,, 1 ,,,, 0 ,,,, 0 ,,,,-1 ,-1 ,-1 , 0 , 0 , 0 , 0 , 0
BR U #Sta/Elev= 69
  4060.6    70.8  4090.6    70.7  4150.6    69.7  4360.6    69.6  4390.6    70.2
  4460.6    69.6  4469.7   69.96  4480.6    70.4  4529.6    69.4  4679.6    68.8
  4689.6    69.3  4861.5   68.81  4893.4   68.99  4943.7   69.47  4966.3   69.61
  4983.6   69.72    4986   64.45 4986.11   64.21  4986.2   64.01 4986.29   63.82
  4986.4   63.57 4986.51   63.33  4987.7   60.72  4987.8   60.74  4992.3    61.8
    4994   60.85  4996.2   60.88  5001.4   61.59  5007.6   62.65  5015.9   67.43
    5016   67.74  5016.5   69.27 5016.56   69.27 5016.67   69.28 5016.78   69.29
 5016.89    69.3    5017    69.3    5018   69.37  5033.7   69.47  5064.6   69.67
  5101.7   69.64  5133.1   69.62  5158.6    69.7  5178.6    69.2  5298.6      70
  5348.6    69.9  5358.6    70.2  5368.6    68.9  5398.6    66.6  5408.6    67.9
  5458.6    68.4  5478.6    69.3  5538.6    69.5  5558.6    68.8  5588.6    69.5
  5598.6    68.9  5658.6      70  5708.6    69.5  5798.6    70.2  5799.7    70.2
  5908.6    69.9  6018.6    69.4  6038.6      69  6158.6    69.6  6398.6      70
  6428.6    69.7  6538.6    69.7  6548.9      70  6550.6      71
BR U #Mann= 5
  4060.6     .99  4469.7      .1  4983.6     .04  5016.5      .1  5799.7     .99
BR U Banks=4983.6,5016.5
BR D #Sta/Elev= 69
  4060.6   70.72  4090.6   70.62  4150.6   69.62  4360.6   69.52  4390.6   70.12
  4460.6   69.52  4469.7   69.88  4480.6   70.32  4529.6   69.32  4679.6   68.72
  4689.6   69.22  4861.5   68.73  4893.4   68.91  4943.7   69.39  4966.3   69.53
  4983.6   69.64    4986   64.37 4986.11   64.13  4986.2   63.93 4986.29   63.74
  4986.4   63.49 4986.51   63.25  4987.7   60.64  4987.8   60.66  4992.3   61.72
    4994   60.77  4996.2    60.8  5001.4   61.51  5007.6   62.57  5015.9   67.35
    5016   67.66  5016.5   69.19 5016.56   69.19 5016.67    69.2 5016.78   69.21
 5016.89   69.22    5017   69.22    5018   69.29  5033.7   69.39  5064.6   69.59
  5101.7   69.56  5133.1   69.54  5158.6   69.62  5178.6   69.12  5298.6   69.92
  5348.6   69.82  5358.6   70.12  5368.6   68.82  5398.6   66.52  5408.6   67.82
  5458.6   68.32  5478.6   69.22  5538.6   69.42  5558.6   68.72  5588.6   69.42
  5598.6   68.82  5658.6   69.92  5708.6   69.42  5798.6   70.12  5799.7   70.12
  5908.6   69.82  6018.6   69.32  6038.6   68.92  6158.6   69.52  6398.6   69.92
  6428.6   69.62  6538.6   69.62  6548.9   69.92  6550.6   70.92
BR D #Mann= 5
  4060.6     .99  4469.7      .1  4983.6     .04  5016.5      .1  5799.7     .99
BR D Banks=4983.6,5016.5
BC Design=,, 0 ,, 0 ,,,,,,

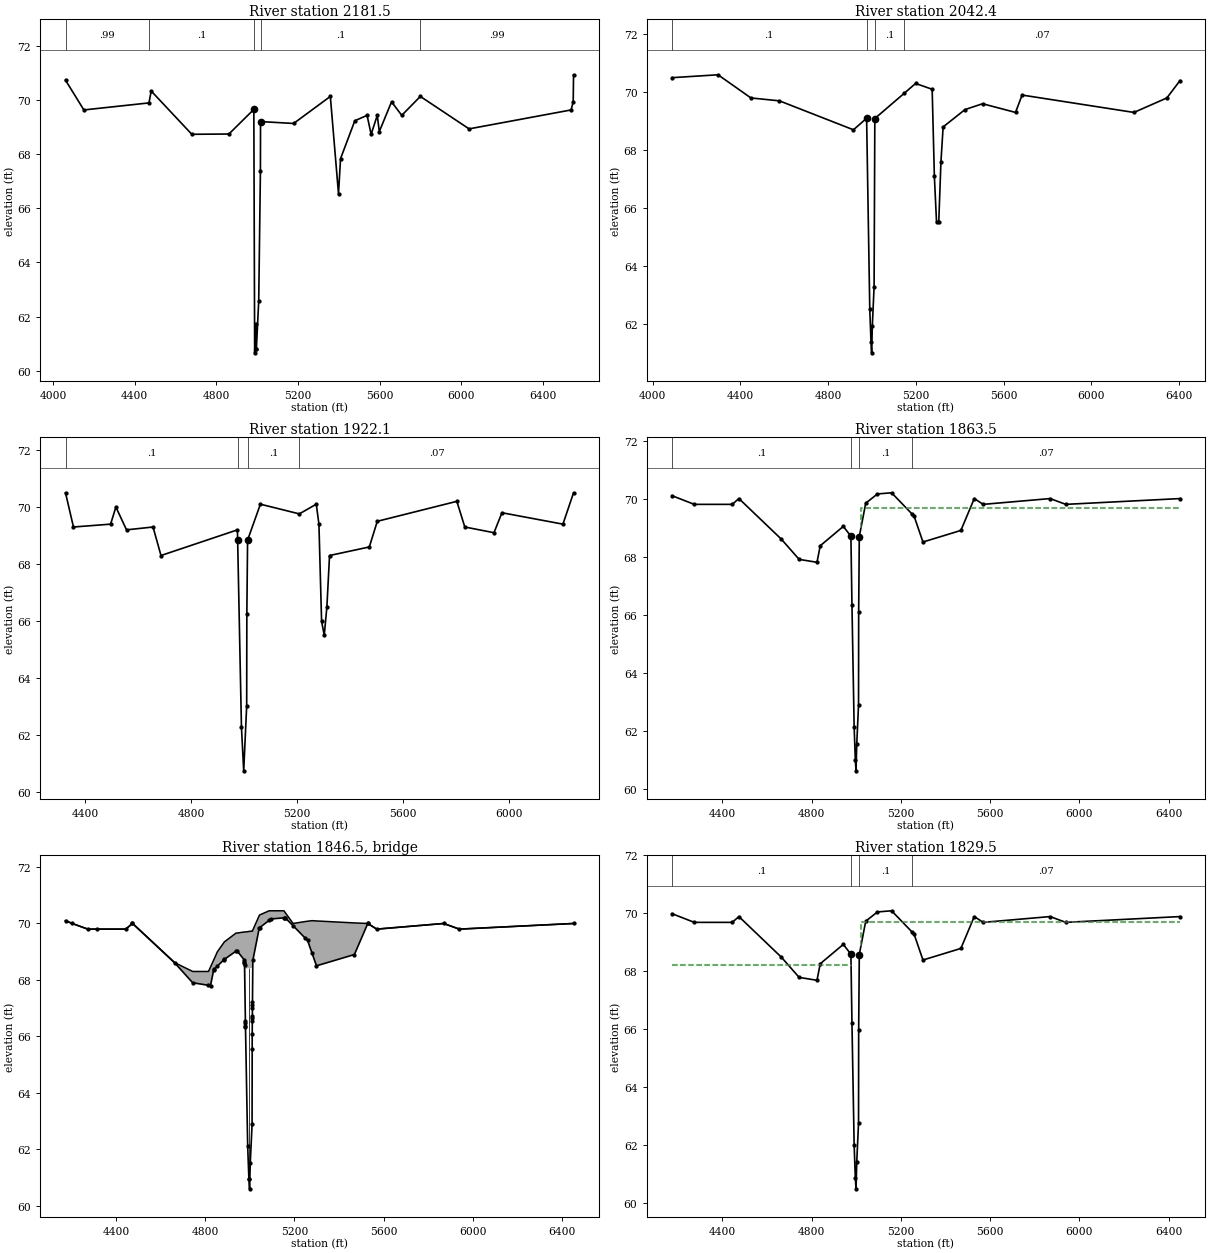
Type RM Length L Ch R = 1 ,2181.5  ,139.1,139.1,139.1
BEGIN DESCRIPTION:
Downstream Section of Bridge/Culvert/Weir
END DESCRIPTION:
XS GIS Cut Line= 6
      3116134.42     13888326.97      3116594.26     13888324.62
      3116942.02     13888223.16      3117047.29     13888149.34
      3117109.15     13888117.53      3118574.53     13888004.32
#Sta/Elev= 30
  4060.6   70.74  4150.6   69.64  4469.7    69.9  4480.6   70.34  4679.6   68.74
  4861.5   68.75  4983.6   69.66  4987.7   60.66  4992.3   61.74    4994   60.79
  4996.2   60.82  5007.6   62.59  5015.9   67.37  5016.5   69.21  5178.6   69.14
  5358.6   70.14  5398.6   66.54  5408.6   67.84  5478.6   69.24  5538.6   69.44
  5558.6   68.74  5588.6   69.44  5598.6   68.84  5658.6   69.94  5708.6   69.44
  5799.7   70.14  6038.6   68.94  6538.6   69.64  6548.9   69.94  6550.6   70.94
#Mann= 5 , 1 , 0
  4060.6     .99       0  4469.7      .1       0  4983.6     .04       0
  5016.5      .1       0  5799.7     .99       0
#XS Ineff= 2 , 0
       0    4976    68.6    5027       0    67.7
Permanent Ineff=
       F       F
Bank Sta=4983.6,5016.5
XS Rating Curve= 0
Exp/Cntr=.5,.3

Type RM Length L Ch R = 1 ,2042.4  ,78.7,120.3,27.8
BEGIN DESCRIPTION:
Cross Section 2042.4-Interpolated
END DESCRIPTION:
XS GIS Cut Line= 5
      3116232.18     13888383.15      3116829.57     13888388.93
      3117121.24     13888274.55      3117327.12     13888160.17
      3118493.96     13888073.34
#Sta/Elev= 27
  4088.4    70.5  4298.4    70.6  4448.4    69.8  4578.4    69.7  4915.9    68.7
  4975.8    69.1  4990.2   62.52  4995.9   61.36  4998.7      61  5001.8   61.91
  5009.9   63.28  5013.3   69.09  5147.1   69.96  5199.1    70.3  5274.7    70.1
  5284.7    67.1  5294.7    65.5  5304.7    65.5  5314.7    67.6  5324.7    68.8
  5424.7    69.4  5504.7    69.6  5654.7    69.3  5684.7    69.9  6194.7    69.3
  6344.7    69.8  6404.7    70.4
#Mann= 4 , 1 , 0
  4088.4      .1       0  4975.8     .04       0  5013.3      .1       0
  5147.1     .07       0
#XS Ineff= 2 , 0
       0                  5684.7       0    69.9
Permanent Ineff=
       F       F
Bank Sta=4975.8,5013.3
XS Rating Curve= 0
Exp/Cntr=.3,.1

Type RM Length L Ch R = 1 ,1922.1  ,48.7,58.6,37.7
BEGIN DESCRIPTION:
Cross Section 1922.1-Interpolated
END DESCRIPTION:
XS GIS Cut Line= 5
      3116542.08     13888456.49      3117090.26     13888445.15
      3117241.66     13888336.14      3117320.38     13888184.74
      3118327.89     13888113.86
#Sta/Elev= 30
  4326.8    70.5  4356.8    69.3  4496.8    69.4  4516.8      70  4556.8    69.2
  4656.8    69.3  4686.8    68.3  4975.1    69.2  4975.8   68.85  4990.2   62.27
  4998.7   60.75  5009.9   63.03  5010.5   66.24  5013.3   68.84  5061.6    70.1
  5208.4   69.76  5272.3    70.1  5282.3    69.4  5292.3      66  5302.3    65.5
  5312.3    66.5  5322.3    68.3  5472.3    68.6  5502.3    69.5  5802.3    70.2
  5832.3    69.3  5942.3    69.1  5972.3    69.8  6202.3    69.4  6242.3    70.5
#Mann= 4 , 1 , 0
  4326.8      .1       0  4975.8     .04       0  5013.3      .1       0
  5208.4     .07       0
#XS Ineff= 2 , 0
       0  4516.8      70  5802.3       0    70.2
Permanent Ineff=
       F       F
Bank Sta=4975.8,5013.3
XS Rating Curve= 0
Exp/Cntr=.5,.3

Type RM Length L Ch R = 1 ,1863.5  ,34,34,34
BEGIN DESCRIPTION:
Upstream Section of Bridge/Culvert/Weir
END DESCRIPTION:
XS GIS Cut Line= 6
      3116451.59     13888523.49      3117110.35     13888531.48
      3117123.92      13888489.2      3117304.74     13888364.26
       3117351.7     13888225.55      3118555.01     13888183.51
#Sta/Elev= 30
  4173.8   70.12  4273.8   69.82  4443.8   69.82  4473.8   70.02  4663.8   68.62
  4743.8   67.92  4823.8   67.82  4838.1   68.39  4941.7   69.06  4975.7   68.72
  4980.4   66.35  4990.2   62.14  4995.6   60.98  4998.7   60.62  5001.8   61.53
  5009.9    62.9  5010.5   66.11  5013.3   68.71  5042.1   69.86  5094.7   70.18
  5158.1   70.22  5249.3   69.49  5258.6   69.42  5298.6   68.52  5468.6   68.92
  5528.5   70.02  5568.6   69.82  5868.6   70.02  5938.6   69.82  6450.6   70.02
#Mann= 4 , 1 , 0
  4173.8      .1       0  4975.7     .04       0  5013.3      .1       0
  5249.3     .07       0
#XS Ineff= 2 , 0
       0  4976.5    68.3    5021       0    69.7
Permanent Ineff=
       F       F
Bank Sta=4975.7,5013.3
XS Rating Curve= 0
Exp/Cntr=.5,.3

Type RM Length L Ch R = 3 ,1846.5  ,,,
BEGIN DESCRIPTION:
BAUMAN ROAD
Structure ID: P83-3,,,,
END DESCRIPTION:
Bridge Culvert--1,0,-1,-1, 0
Deck Dist Width WeirC Skew NumUp NumDn MinLoCord MaxHiCord MaxSubmerge Is_Ogee
10,14,2.6,0, 60, 60, , , .95, 0, 1,1,,
  4173.8  4203.8  4273.8  4313.8  4443.8  4473.7  4473.8  4663.8  4743.8  4814.5
  4823.8  4838.1  4838.2  4854.5  4884.2    4886    4938  4941.7  4975.7 4975.79
  4975.9 4976.01 4980.01  4980.1  4980.3  4980.4  4990.2  4995.6  4995.9  4998.7
  5001.8  5009.9  5010.4  5010.5 5010.99  5011.1  5011.2 5011.49  5011.6 5011.71
  5013.3  5042.1  5043.4  5086.3  5094.7    5153    5158  5158.1  5193.8  5249.3
  5258.6    5278  5298.6  5468.6  5528.5  5528.6  5568.6  5868.6  5938.6  6450.6
    70.1      70    69.8    69.8    69.8      70   70.01   68.61    68.3    68.3
   68.46   68.71   68.71      69   69.33   69.35   69.66   69.66    69.7    69.7
    69.7    69.7    69.7    69.7    69.7    69.7   69.71   69.72   69.72   69.72
   69.72   69.73   69.73   69.73   69.73   69.73   69.73   69.74   69.74   69.74
   69.77   70.28    70.3   70.45   70.45   70.45   70.39   70.39      70   70.07
   70.08    70.1   70.09   70.02      70      70    69.8      70    69.8      70
    70.1      70    69.8    69.8    69.8      70      70    68.6    67.9   67.81
    67.8   68.37   68.36   68.49   68.72   68.73   69.02   69.04    68.7   68.65
    68.6   68.54   66.53    68.4    68.4    68.4   68.41   68.42   68.42   68.42
   68.42   68.43   68.43   68.43   68.43   66.65   66.74   67.01   67.11   67.21
   68.69   69.84   69.85   70.11   70.16    70.2    70.2    70.2   69.92   69.47
    69.4   68.96    68.5    68.9      70      70    69.8      70    69.8      70
  4173.8  4203.8  4273.8  4313.8  4443.8  4473.7  4473.8  4663.8  4743.8  4814.5
  4823.8  4838.1  4838.2  4854.5  4884.2    4886    4938  4941.7  4975.7 4975.79
  4975.9 4976.01 4980.01  4980.1  4980.3  4980.4  4990.2  4995.6  4995.9  4998.7
  5001.8  5009.9  5010.4  5010.5 5010.99  5011.1  5011.2 5011.49  5011.6 5011.71
  5013.3  5042.1  5043.4  5086.3  5094.7    5153    5158  5158.1  5193.8  5249.3
  5258.6    5278  5298.6  5468.6  5528.5  5528.6  5568.6  5868.6  5938.6  6450.6
    70.1      70    69.8    69.8    69.8      70   70.01   68.61    68.3    68.3
   68.46   68.71   68.71      69   69.33   69.35   69.66   69.66    69.7    69.7
    69.7    69.7    69.7    69.7    69.7    69.7   69.71   69.72   69.72   69.72
   69.72   69.73   69.73   69.73   69.73   69.73   69.73   69.74   69.74   69.74
   69.77   70.28    70.3   70.45   70.45   70.45   70.39   70.39      70   70.07
   70.08    70.1   70.09   70.02      70      70    69.8      70    69.8      70
      70    69.9    69.7    69.7    69.7    69.9    69.9    68.5    67.8   67.71
    67.7   68.27   68.26   68.39   68.62   68.63   68.92   68.94    68.6   68.55
    68.5   68.44   66.43    68.3    68.3    68.3   68.31   68.32   68.32   68.32
   68.32   68.33   68.33   68.33   68.33   66.55   66.64   66.91   67.01   67.11
   68.59   69.74   69.75   70.01   70.06    70.1    70.1    70.1   69.82   69.37
    69.3   68.86    68.4    68.8    69.9    69.9    69.7    69.9    69.7    69.9
Pier Skew, UpSta & Num, DnSta & Num=  ,4995.6, 2 ,4995.6, 2 , 0 , 0 , 0 ,,
       1       1
   59.93   69.42
       1       1
   59.83   69.32
BR Coef= 1 , 1 , 0 ,1.25, 0 ,,,.8,0,2,0,
WSPro=,,,, 1 ,,,, 0 ,,,, 0 ,,,,-1 ,-1 ,-1 , 0 , 0 , 0 , 0 , 0
BR U #Sta/Elev= 60
  4173.8    70.1  4203.8      70  4273.8    69.8  4313.8    69.8  4443.8    69.8
  4473.7      70  4473.8      70  4663.8    68.6  4743.8    67.9  4814.5   67.81
  4823.8    67.8  4838.1   68.37  4838.2   68.36  4854.5   68.49  4884.2   68.72
    4886   68.73    4938   69.02  4941.7   69.04  4975.7    68.7 4975.79   68.65
  4975.9    68.6 4976.01   68.54 4980.01   66.53  4980.1   66.48  4980.3   66.38
  4980.4   66.33  4990.2   62.12  4995.6   60.96  4995.9   60.96  4998.7    60.6
  5001.8   61.51  5009.9   62.88  5010.4   65.55  5010.5   66.09 5010.99   66.55
  5011.1   66.65  5011.2   66.74 5011.49   67.01  5011.6   67.11 5011.71   67.21
  5013.3   68.69  5042.1   69.84  5043.4   69.85  5086.3   70.11  5094.7   70.16
    5153    70.2    5158    70.2  5158.1    70.2  5193.8   69.92  5249.3   69.47
  5258.6    69.4    5278   68.96  5298.6    68.5  5468.6    68.9  5528.5      70
  5528.6      70  5568.6    69.8  5868.6      70  5938.6    69.8  6450.6      70
BR U #Mann= 4
  4173.8      .1  4975.7     .04  5013.3      .1  5249.3     .07
BR U Banks=4975.7,5013.3
BR D #Sta/Elev= 60
  4173.8      70  4203.8    69.9  4273.8    69.7  4313.8    69.7  4443.8    69.7
  4473.7    69.9  4473.8    69.9  4663.8    68.5  4743.8    67.8  4814.5   67.71
  4823.8    67.7  4838.1   68.27  4838.2   68.26  4854.5   68.39  4884.2   68.62
    4886   68.63    4938   68.92  4941.7   68.94  4975.7    68.6 4975.79   68.55
  4975.9    68.5 4976.01   68.44 4980.01   66.43  4980.1   66.38  4980.3   66.28
  4980.4   66.23  4990.2   62.02  4995.6   60.86  4995.9   60.86  4998.7    60.5
  5001.8   61.41  5009.9   62.78  5010.4   65.45  5010.5   65.99 5010.99   66.45
  5011.1   66.55  5011.2   66.64 5011.49   66.91  5011.6   67.01 5011.71   67.11
  5013.3   68.59  5042.1   69.74  5043.4   69.75  5086.3   70.01  5094.7   70.06
    5153    70.1    5158    70.1  5158.1    70.1  5193.8   69.82  5249.3   69.37
  5258.6    69.3    5278   68.86  5298.6    68.4  5468.6    68.8  5528.5    69.9
  5528.6    69.9  5568.6    69.7  5868.6    69.9  5938.6    69.7  6450.6    69.9
BR D #Mann= 4
  4173.8      .1  4975.7     .04  5013.3      .1  5249.3     .07
BR D Banks=4975.7,5013.3
BC Design=,, 0 ,, 0 ,,,,,,

Type RM Length L Ch R = 1 ,1829.5  ,218.1,218.1,218.1
BEGIN DESCRIPTION:
Downstream Section of Bridge/Culvert/Weir
END DESCRIPTION:
XS GIS Cut Line= 6
      3116471.21     13888551.26      3117129.97     13888559.26
      3117143.54     13888516.98      3117324.36     13888392.04
      3117371.32     13888253.33      3118574.62     13888211.28
#Sta/Elev= 30
  4173.8   69.98  4273.8   69.68  4443.8   69.68  4473.8   69.88  4663.8   68.48
  4743.8   67.78  4823.8   67.68  4838.1   68.25  4941.7   68.92  4975.7   68.58
  4980.4   66.21  4990.2      62  4995.6   60.84  4998.7   60.48  5001.8   61.39
  5009.9   62.76  5010.5   65.97  5013.3   68.57  5042.1   69.72  5094.7   70.04
  5158.1   70.08  5249.3   69.35  5258.6   69.28  5298.6   68.38  5468.6   68.78
  5528.5   69.88  5568.6   69.68  5868.6   69.88  5938.6   69.68  6450.6   69.88
#Mann= 4 , 1 , 0
  4173.8      .1       0  4975.7     .04       0  5013.3      .1       0
  5249.3     .07       0
#XS Ineff= 2 , 0
       0  4976.5    68.2    5021       0    69.7
Permanent Ineff=
       F       F
Bank Sta=4975.7,5013.3
XS Rating Curve= 0
Exp/Cntr=.5,.3