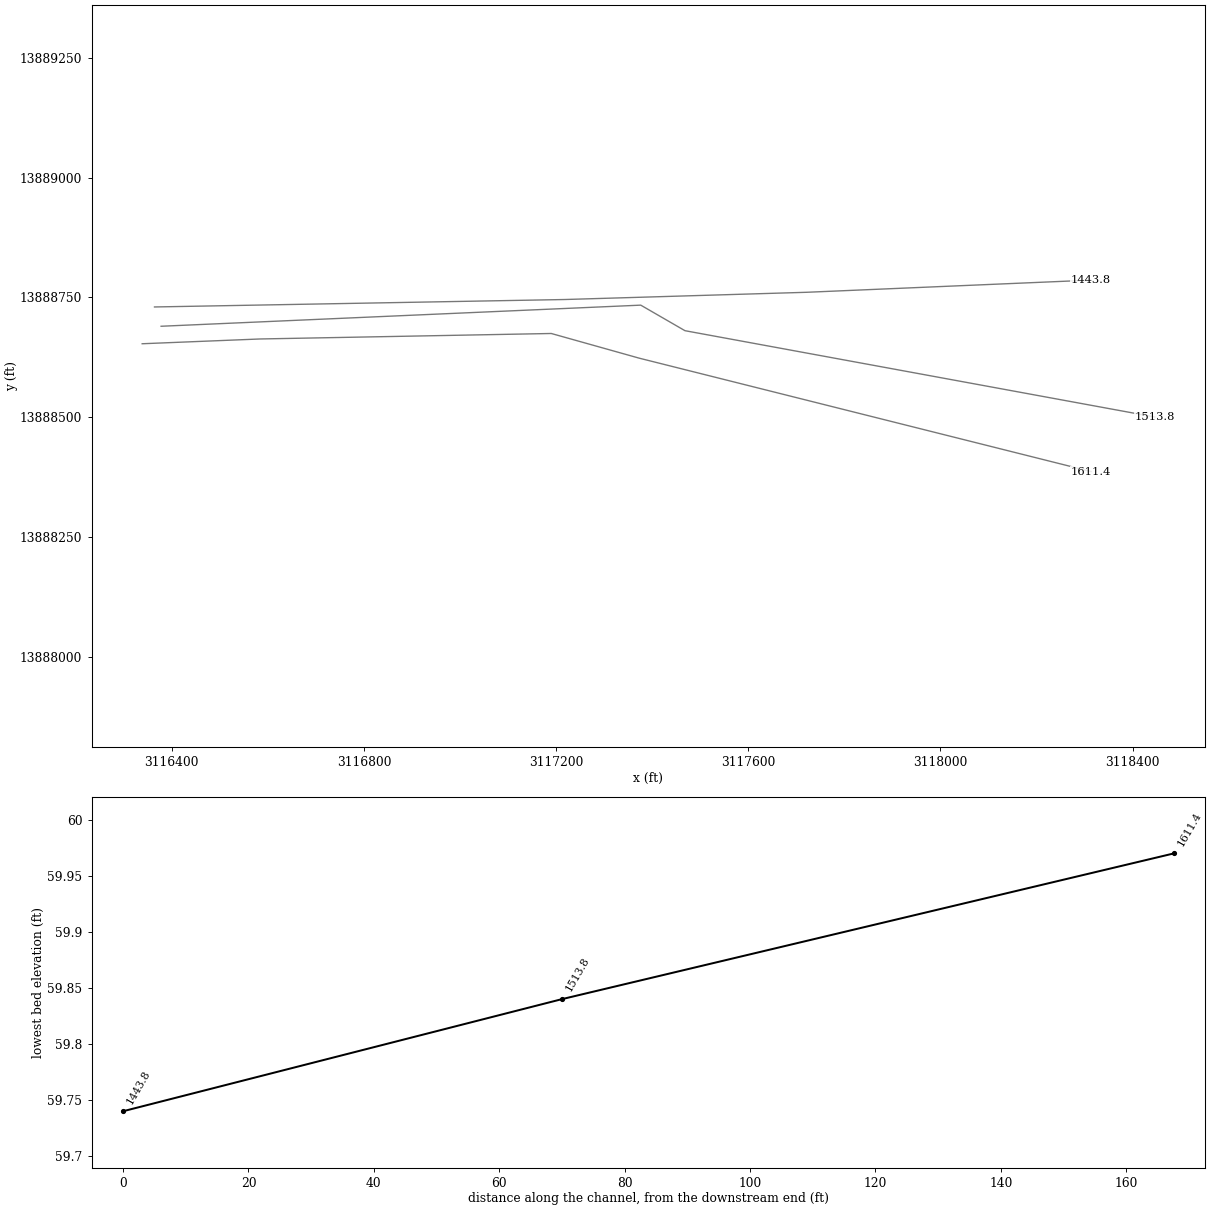
HEC-RAS study P118-23-00.PRJ: P118-23-00

--- P118-23-00.g01 (geometry) --- (continued)

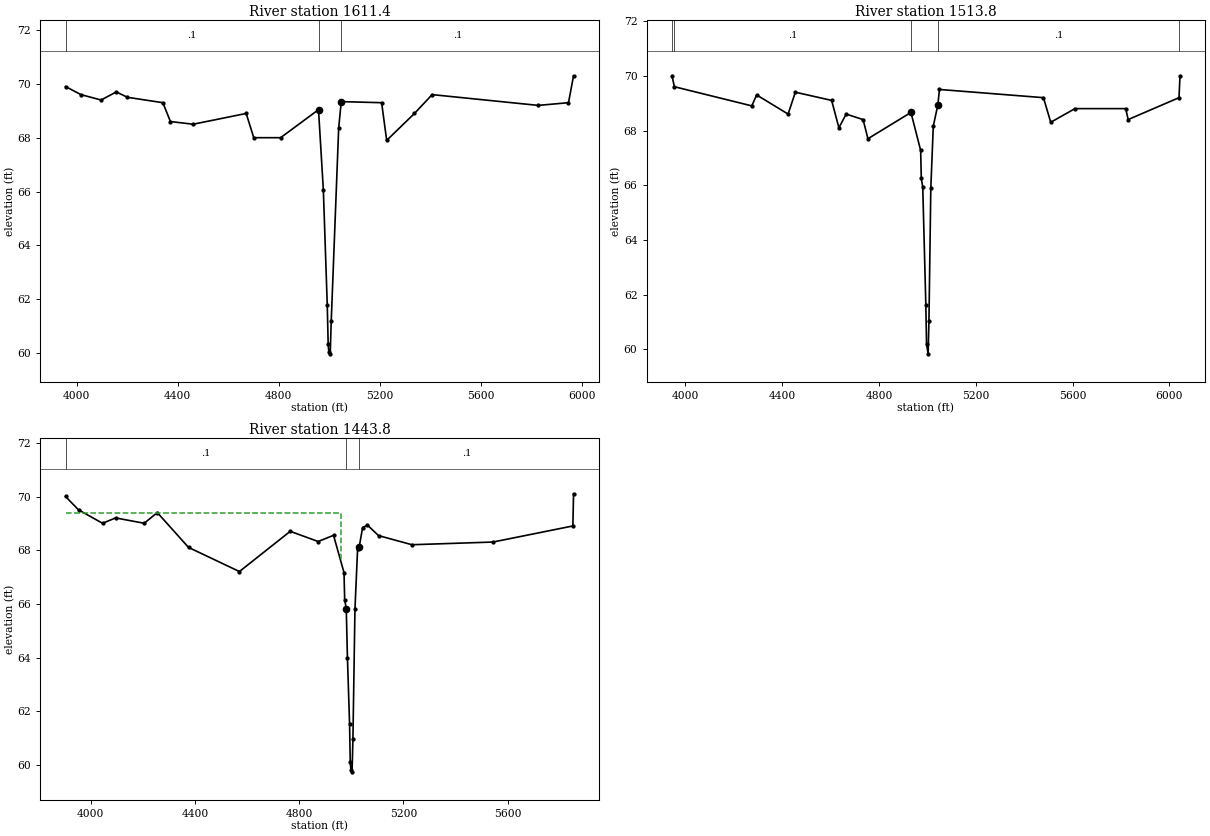
Type RM Length L Ch R = 1 ,1611.4  ,49.9,97.6,107.2
BEGIN DESCRIPTION:
Cross Section 1611.4-Interpolated
END DESCRIPTION:
XS GIS Cut Line= 5
      3116338.34     13888653.48      3116583.66     13888663.44
      3117189.86     13888674.88      3117372.87     13888623.41
      3118313.53     13888386.83
#Sta/Elev= 27
  3955.6    69.9  4016.6    69.6  4096.6    69.4  4156.6    69.7  4201.1    69.5
  4341.1    69.3  4371.1    68.6  4461.1    68.5  4671.1    68.9  4701.1      68
  4807.4      68  4957.5   69.04  4976.7   66.06  4992.2   61.77  4995.8   60.32
  4998.5   60.04  5003.9   59.97  5007.9   61.18  5037.4   68.36  5047.6   69.34
  5207.5    69.3  5227.5    67.9  5337.5    68.9  5407.5    69.6  5827.5    69.2
  5947.5    69.3  5967.5    70.3
#Mann= 3 , 1 , 0
  3955.6      .1       0  4957.5     .04       0  5047.6      .1       0
Bank Sta=4957.5,5047.6
XS Rating Curve= 0
Exp/Cntr=.3,.1

Type RM Length L Ch R = 1 ,1513.8  ,28.5,70,177.4
BEGIN DESCRIPTION:
Cross Section 1513.8-Interpolated
END DESCRIPTION:
XS GIS Cut Line= 4
      3116377.75     13888689.97      3117376.09     13888734.01
      3117468.14     13888680.72      3118446.03      13888500.7
#Sta/Elev= 30
  3944.3      70  3954.3    69.6  4274.3    68.9  4294.3    69.3  4424.3    68.6
  4454.3    69.4  4604.3    69.1  4634.3    68.1  4664.3    68.6  4734.3    68.4
  4754.3    67.7  4932.1   68.66 4972.28   67.27 4974.83   66.26 4980.89   65.93
  4993.6   61.64 4996.56   60.19  5003.2   59.84 5006.48   61.05 5014.27    65.9
 5024.44   68.16 5043.62   68.95  5049.9    69.5  5479.9    69.2  5509.9    68.3
  5609.9    68.8  5819.9    68.8  5829.9    68.4  6040.1    69.2  6044.3      70
#Mann= 5 , 1 , 0
  3944.3      .2       0  3954.3      .1       0  4932.1     .04       0
 5043.62      .1       0  6040.1      .2       0
#XS Ineff= 2 , 0
       0  4454.3    69.4  5479.9       0    69.2
Permanent Ineff=
       F       F
Bank Sta=4932.1,5043.62
XS Rating Curve= 0
Exp/Cntr=.5,.3

Type RM Length L Ch R = 1 ,1443.8  ,58,58,58
BEGIN DESCRIPTION:
Upstream Section of Bridge/Culvert/Weir
END DESCRIPTION:
XS GIS Cut Line= 4
      3116363.98     13888730.22      3117217.38     13888745.73
      3117721.29     13888760.82      3118313.07     13888786.19
#Sta/Elev= 30
  3903.3   70.01  3953.3   69.51  4045.5   69.01  4095.5   69.21  4205.5   69.01
  4255.5   69.41  4375.5   68.11  4570.8   67.21  4765.9   68.71  4872.9   68.33
  4932.1   68.56 4972.28   67.17 4974.83   66.16 4980.89   65.83  4985.4      64
  4993.6   61.54 4996.26   60.09 4998.77   59.81  5003.2   59.74 5006.48   60.95
 5014.27    65.8 5024.44   68.06 5030.67   68.13 5043.62   68.85 5062.24   68.94
 5104.88   68.55  5232.9   68.21  5543.9   68.31  5850.7   68.91  5853.3   70.11
#Mann= 3 , 1 , 0
  3903.3      .1       0 4980.89     .04       0 5030.67      .1       0
#XS Ineff= 2 , 0
       0    4961    69.4    5032       0    68.2
Permanent Ineff=
       F       F
Bank Sta=4980.89,5030.67
XS Rating Curve= 0
Exp/Cntr=.5,.3