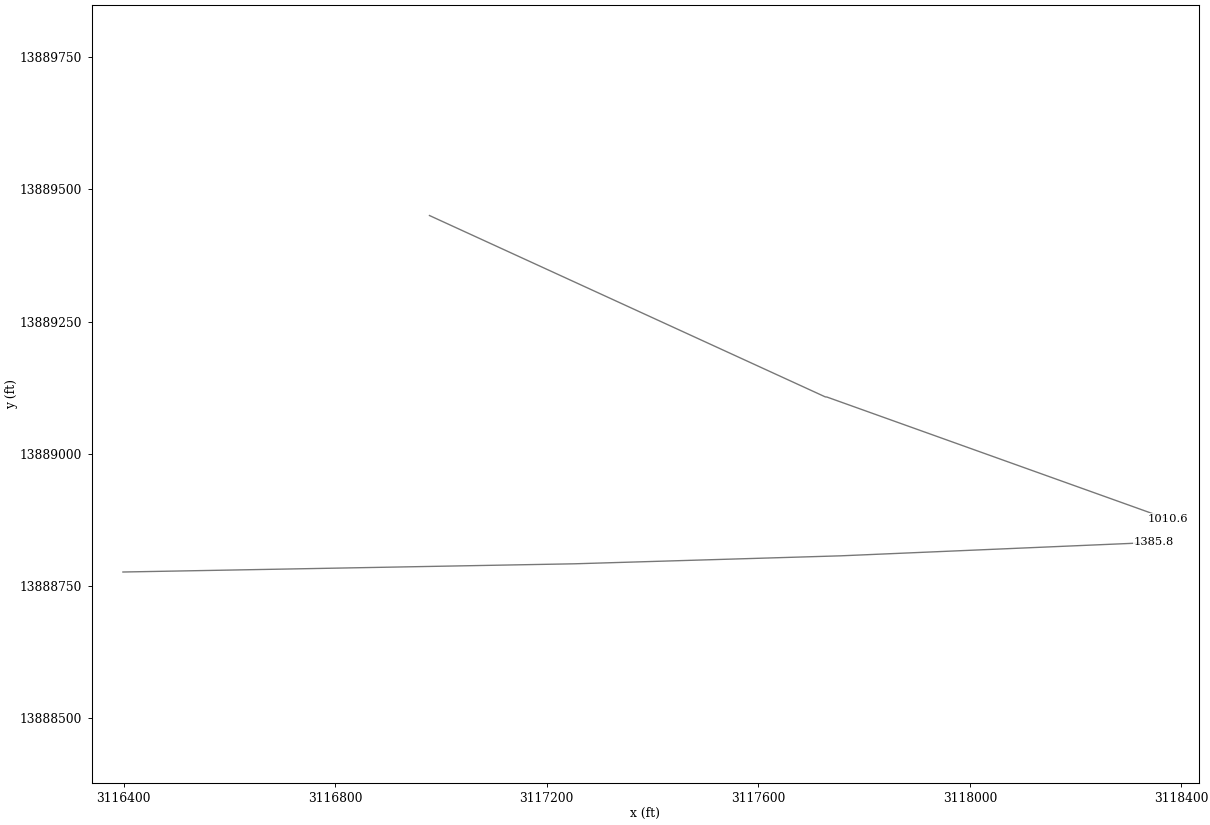
HEC-RAS study P118-23-00.PRJ: P118-23-00

--- P118-23-00.g01 (geometry) --- (continued)

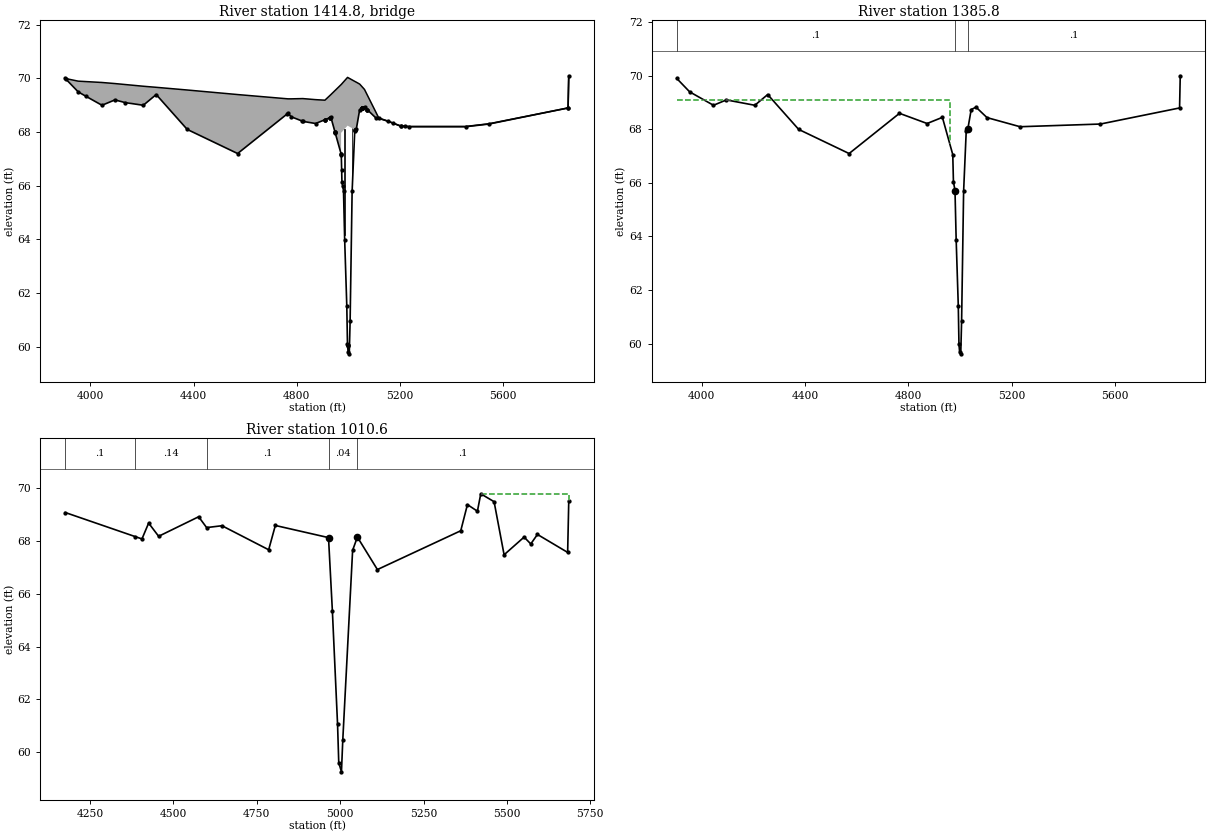
Type RM Length L Ch R = 3 ,1414.8  ,,,
BEGIN DESCRIPTION:
GULF BANK ROAD, SKEW ANGLE OF 35 DEGREES
Structure ID: P83-2,,,,
END DESCRIPTION:
Bridge Culvert--1,0,-1,-1, 0
Deck Dist Width WeirC Skew NumUp NumDn MinLoCord MaxHiCord MaxSubmerge Is_Ogee
10,38,2.6,0, 29, 29, , , .95, 0, 1,1,,
  3903.3  3953.3  4045.5  4095.5  4205.5  4255.5  4375.5  4570.8  4765.9  4778.6
 4822.96  4872.9 4908.91  4932.1 4971.52 4971.61 4996.61 5026.69 5030.67 5043.62
 5062.24 5104.88  5117.3 5202.46  5232.9  5453.9  5543.9  5850.7  5853.3
      70    69.9   69.85   69.81   69.71   69.67   69.57    69.4   69.24   69.24
   69.25   69.21   69.19    69.4   69.77   69.77   70.04   69.88   69.86   69.79
   69.59   68.77   68.53   68.23   68.21   68.21   68.31    68.9    70.1
      70    69.5      69    69.2      69    69.4    68.1    67.2    68.7   68.57
    68.4   68.32   68.46   68.55   67.19   67.97   68.24   68.08   68.12   68.84
   68.93   68.54   68.51   68.22    68.2    68.2    68.3    68.9    70.1
  3903.3  3953.3  4045.5  4095.5  4205.5  4255.5  4375.5  4570.8  4765.9  4778.6
 4822.96  4872.9 4908.91  4932.1 4971.52 4971.61 4996.61 5026.69 5030.67 5043.62
 5062.24 5104.88  5117.3 5202.46  5232.9  5453.9  5543.9  5850.7  5853.3
      70    69.9   69.85   69.81   69.71   69.67   69.57    69.4   69.24   69.24
   69.25   69.21   69.19    69.4   69.77   69.77   70.04   69.88   69.86   69.79
   69.59   68.77   68.53   68.23   68.21   68.21   68.31    68.9    70.1
    69.9    69.4    68.9    69.1    68.9    69.3      68    67.1    68.6   68.47
    68.3   68.22   68.36   68.45   67.09   67.87   68.14   67.98   68.02   68.74
   68.83   68.44   68.41   68.12    68.1    68.1    68.2    68.8      70
Pier Skew, UpSta & Num, DnSta & Num=  ,4985, 2 ,4985, 2 , 0 , 0 , 0 ,,
     1.3     1.3
    62.9   69.12
     1.3     1.3
    62.8   69.02
Pier Skew, UpSta & Num, DnSta & Num=  ,5014.6, 2 ,5014.6, 2 , 0 , 0 , 0 ,,
     1.3     1.3
    64.6   69.14
     1.3     1.3
    64.5   69.04
Abutment Skew #Up #Dn= , 2 , 2
 4971.41 4977.91
   67.97   65.98
 4971.41 4977.91
   67.87   65.88
Abutment Skew #Up #Dn= , 2 , 2
 5025.03 5026.89
   68.06   68.08
 5025.03 5026.89
   67.96   67.98
BR Coef= 1 , 1 , 0 ,1.25, 0 ,,,.8,0,2,0,
WSPro=,,,, 1 ,,,, 0 ,,,, 0 ,,,,-1 ,-1 ,-1 , 0 , 0 , 0 , 0 , 0
BR U #Sta/Elev= 75
  3903.3      70  3904.2   69.99  3953.3    69.5  3984.2   69.33  4045.5      69
  4095.5    69.2  4135.5    69.1  4205.5      69  4255.5    69.4  4375.5    68.1
  4570.8    67.2  4761.8   68.67  4765.9    68.7  4778.6   68.57  4821.1   68.41
 4822.96    68.4  4872.9   68.32 4908.69   68.46  4908.8   68.46 4908.91   68.46
 4928.89   68.54    4929   68.54 4929.11   68.54  4932.1   68.55  4947.7   68.01
 4948.29   67.99  4948.4   67.99 4948.51   67.98 4971.52   67.19 4971.61   67.18
 4972.28   67.16  4973.7    66.6 4974.83   66.15 4977.91   65.98 4980.89   65.82
  4985.4   63.99  4993.6   61.53 4996.26   60.08 4996.39   60.07  4996.5   60.05
 4996.61   60.04 4998.77    59.8  5003.2   59.73 5006.48   60.94 5014.27   65.79
 5024.44   68.05 5025.03   68.06 5026.69   68.08  5026.8   68.08 5030.67   68.12
 5043.62   68.84 5052.19   68.88  5052.3   68.88 5052.41   68.88 5052.49   68.88
  5052.6   68.88 5052.71   68.88  5057.9   68.91 5062.24   68.93 5072.29   68.84
  5072.4   68.84 5072.51   68.84 5104.88   68.54  5117.3   68.51 5152.52   68.41
  5173.5   68.33 5202.46   68.22 5202.54   68.22  5220.2   68.21  5232.9    68.2
  5453.9    68.2  5543.9    68.3  5850.2    68.9  5850.7    68.9  5853.3    70.1
BR U #Mann= 3
  3903.3      .1 4980.89     .04 5030.67      .1
BR U Banks=4980.89,5030.67
BR D #Sta/Elev= 75
  3903.3    69.9  3904.2   69.89  3953.3    69.4  3984.2   69.23  4045.5    68.9
  4095.5    69.1  4135.5      69  4205.5    68.9  4255.5    69.3  4375.5      68
  4570.8    67.1  4761.8   68.57  4765.9    68.6  4778.6   68.47  4821.1   68.31
 4822.96    68.3  4872.9   68.22 4908.69   68.36  4908.8   68.36 4908.91   68.36
 4928.89   68.44    4929   68.44 4929.11   68.44  4932.1   68.45  4947.7   67.91
 4948.29   67.89  4948.4   67.89 4948.51   67.88 4971.52   67.09 4971.61   67.08
 4972.28   67.06  4973.7    66.5 4974.83   66.05 4977.91   65.88 4980.89   65.72
  4985.4   63.89  4993.6   61.43 4996.26   59.98 4996.39   59.97  4996.5   59.95
 4996.61   59.94 4998.77    59.7  5003.2   59.63 5006.48   60.84 5014.27   65.69
 5024.44   67.95 5025.03   67.96 5026.69   67.98  5026.8   67.98 5030.67   68.02
 5043.62   68.74 5052.19   68.78  5052.3   68.78 5052.41   68.78 5052.49   68.78
  5052.6   68.78 5052.71   68.78  5057.9   68.81 5062.24   68.83 5072.29   68.74
  5072.4   68.74 5072.51   68.74 5104.88   68.44  5117.3   68.41 5152.52   68.31
  5173.5   68.23 5202.46   68.12 5202.54   68.12  5220.2   68.11  5232.9    68.1
  5453.9    68.1  5543.9    68.2  5850.2    68.8  5850.7    68.8  5853.3      70
BR D #Mann= 3
  3903.3      .1 4980.89     .04 5030.67      .1
BR D Banks=4980.89,5030.67
BC Design=,, 0 ,, 0 ,,,,,,

Type RM Length L Ch R = 1 ,1385.8  ,375.2,375.2,375.2
BEGIN DESCRIPTION:
Downstream Section of Bridge/Culvert/Weir
END DESCRIPTION:
XS GIS Cut Line= 4
      3116398.84     13888776.57      3117252.24     13888792.09
      3117756.15     13888807.18      3118347.93     13888832.54
#Sta/Elev= 30
  3903.3   69.89  3953.3   69.39  4045.5   68.89  4095.5   69.09  4205.5   68.89
  4255.5   69.29  4375.5   67.99  4570.8   67.09  4765.9   68.59  4872.9   68.21
  4932.1   68.44 4972.28   67.05 4974.83   66.04 4980.89   65.71  4985.4   63.88
  4993.6   61.42 4996.26   59.97 4998.77   59.69  5003.2   59.62 5006.48   60.83
 5014.27   65.68 5024.44   67.94 5030.67   68.01 5043.62   68.73 5062.24   68.82
 5104.88   68.43  5232.9   68.09  5543.9   68.19  5850.7   68.79  5853.3   69.99
#Mann= 3 , 1 , 0
  3903.3      .1       0 4980.89     .04       0 5030.67      .1       0
#XS Ineff= 2 , 0
       0    4961    69.1    5032       0      68
Permanent Ineff=
       F       F
Bank Sta=4980.89,5030.67
XS Rating Curve= 0
Exp/Cntr=.5,.3

Type RM Length L Ch R = 1 ,1010.6  ,0,0,0
BEGIN DESCRIPTION:
Cross Section 1010.6-Interpolated
END DESCRIPTION:
XS GIS Cut Line= 4
      3116978.41      13889450.5      3117726.74     13889107.62
      3117729.67     13889107.39       3118373.6     13888876.89
#Sta/Elev= 30
  4175.6   69.08  4384.9   68.17  4405.6   68.08  4425.6   68.68  4455.6   68.18
  4575.6   68.92  4599.5   68.51  4645.6   68.58  4785.6   67.67  4805.6   68.59
  4965.1   68.13  4976.7   65.35  4992.2   61.06  4995.8   59.61  5003.9   59.26
  5007.9   60.47  5037.4   67.65  5051.7   68.15  5111.7   66.92  5361.7   68.39
  5381.7   69.38  5411.7   69.13  5421.7   69.79  5461.7   69.49  5491.7   67.48
  5551.7   68.15  5571.7   67.89  5591.7   68.25  5682.3   67.57  5685.6    69.5
#Mann= 5 , 1 , 0
  4175.6      .1       0  4384.9     .14       0  4599.5      .1       0
  4965.1     .04       0  5051.7      .1       0
#XS Ineff= 2 , 0
       0  4575.6   68.92  5421.7       0   69.79
Permanent Ineff=
       F       F
Bank Sta=4965.1,5051.7
XS Rating Curve= 0
Exp/Cntr=.3,.1

Chan Stop Cuts=-1